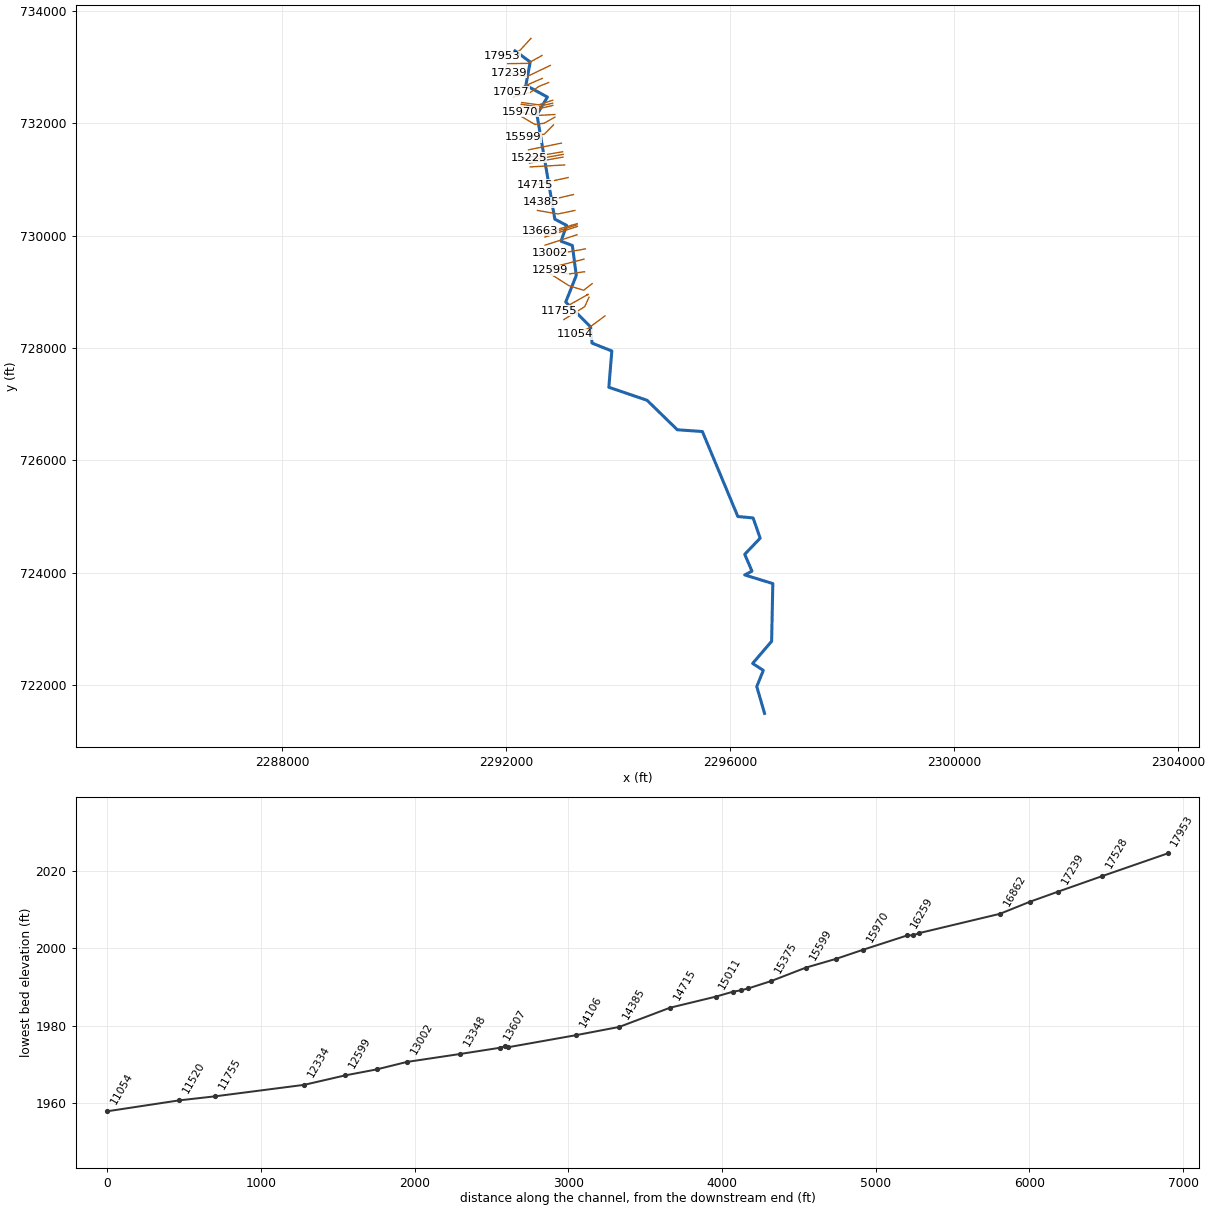
--- PEARCYRN.prj (project) ---

Proj Title=PEARCYRN
Current Plan=p01
Default Exp/Contr=0,0
English Units
Geom File=g01
Flow File=f01
Plan File=p01
BEGIN DESCRIPTION:
----------MODEL BY WOOD PLC 2022----------
AFH study
Randolph County, WV
HEC-RAS Version: RAS 6.2
Vertical Datum: NAVD88
Projection: NAD 1983 StatePlane West Virginia S FIPS 4702 (US Feet)
Terrain: 1-meter LIDAR (FEMA Region III 3DEP collected 2016-2018)
Land Use: 2019 NLCD
Hydrologic Method:
WV SIR2010-5033 regression equations
Additional Model Notes:
None
END DESCRIPTION:
DSS Export Rating Curves= 0
DSS Export Rating Curve Sorted= 0
DSS Export Volume Flow Curves= 0
DXF OffsetX= 0
DXF OffsetY= 0
DXF ScaleX= 0
DXF ScaleY= 0

--- PEARCYRN.p01 (plan) ---

Plan Title=Floodplain
Program Version=6.20
Short Identifier=Floodplain
Geom File=g01
Flow File=f01
Subcritical Flow
K Sum by GR= 0
Std Step Tol= 0.01
Critical Tol= 0.01
Num of Std Step Trials= 20
Max Error Tol= 0.3
Flow Tol Ratio= 0.001
Split Flow NTrial= 30
Split Flow Tol= 0.02
Split Flow Ratio= 0.02
Log Output Level= 0
Friction Slope Method= 1
Unsteady Friction Slope Method= 2
Unsteady Bridges Friction Slope Method= 1
Parabolic Critical Depth
Global Vel Dist= 0 , 0 , 0
Global Log Level= 0
CheckData=True
Encroach Param=-1 ,0,0, 0
Mapping Interval=1HOUR
Computation Time Step Use Courant=        0
Computation Time Step Use Time Series=    0
Computation Time Step Count To Double=0
Computation Time Step Max Doubling=0
Computation Time Step Max Halving=0
Computation Time Step Residence Courant=0
Run HTab= 0
Run UNet= 0
Run Sediment= 0
Run PostProcess= 0
Run WQNet= 0
Run RASMapper=-1
UNET Theta= 0
UNET Theta Warmup= 0
UNET ZTol= 0
UNET ZSATol= 0
UNET MxIter= 0
UNET Max Iter WO Improvement= 0
UNET MaxInSteps= 0
UNET DtIC= 0
UNET DtMin= 0
UNET MaxCRTS= 0
UNET WFStab= 0
UNET SFStab= 0
UNET WFX= 1
UNET SFX= 1
UNET Gravity=32.174
UNET 1D Methodology=Finite Difference
UNET DSS MLevel= 1
UNET Pardiso=0
UNET DZMax Abort= 0
UNET Use Existing IB Tables= 0
UNET Froude Reduction=False
UNET Froude Limit= 0
UNET Froude Power= 0
UNET D1 Cores= 0
UNET WindReference=Eulerian
UNET WindDragFormulation=Hsu (1988)
UNET D2 Coriolis=0
UNET D2 Cores= 0
UNET D2 Theta= 1
UNET D2 Theta Warmup= 1
UNET D2 Z Tol= 0.01
UNET D2 Volume Tol= 0.01
UNET D2 Max Iterations= 20
UNET D2 Equation= 0
UNET D2 RampUpFraction=0.1
UNET D2 TimeSlices= 1
UNET D2 Turbulence Formulation=Non-Conservative (original)
UNET D2 Eddy Viscosity=0.3
UNET D2 Transverse Eddy Viscosity=0.1
UNET D2 Smagorinsky Mixing=0
UNET D2 BCVolumeCheck=0
UNET D2 Cores=0
UNET D2 SolverType=PARDISO (Direct)
UNET D2 Minimum Iterations= 2147483647
UNET D2 Maximum Iterations= 2147483647
UNET D2 Restart Number= 10
UNET D2 Relaxation Coeff=1.3
UNET D2 SOR Precondition Iterations= 10
UNET D2 ILUT Maximum Fill= 8
UNET D2 ILUT Tolerance=1E-08
UNET D1D2 MaxIter= 0
UNET D1D2 ZTol=0.01
UNET D1D2 QTol=0.1
UNET D1D2 MinQTol=1
Write IC File= 0
Write IC File at Fixed DateTime=0
Write IC File at Sim End=0
Echo Input=False
Echo Parameters=False
Echo Output=False
Write Detailed= 0
HDF Write Warmup=0
HDF Write Time Slices=0
HDF Flush=0
HDF Compression= 1
HDF Chunk Size= 1
HDF Spatial Parts= 1
HDF Use Max Rows=0
HDF Fixed Rows= 1
Calibration Method= 0
Calibration Iterations= 20
Calibration Max Change=0.05
Calibration Tolerance=0.2
Calibration Maximum=1.5
Calibration Minimum=0.5
Calibration Optimization Method= 1
WQ AD Non Conservative
WQ ULTIMATE=-1
WQ Max Comp Step=1HOUR
WQ Output Interval=15MIN
WQ Output Selected Increments= 0
WQ Output face flow=0
WQ Output face velocity=0
WQ Output face area=0
WQ Output face dispersion=0
WQ Output cell volume=0
WQ Output cell surface area=0
WQ Output cell continuity=0
WQ Output cumulative cell continuity=0
WQ Output face conc=0
WQ Output face dconc_dx=0
WQ Output face courant=0
WQ Output face peclet=0
WQ Output face adv mass=0
WQ Output face disp mass=0
WQ Output cell mass=0
WQ Output cell source sink temp=0
WQ Output nsm pathways=0
WQ Output nsm derived pathways=0
WQ Create Restart=0
WQ Fixed Restart=0
WQ System Summary=0
WQ Write To DSS=0
Sorting and Armoring Iterations= 10
XS Update Threshold= 0.02
Bed Roughness Predictor= 0
Hydraulics Update Threshold= 0.02
Energy Slope Method= 1
Volume Change Method= 1
Sediment Retention Method= 0
Sediment TS Multiplier= 1
Warm Up Method= 0
XS Weighting Method= 0
Number of US Weighted Cross Sections= 1
Number of DS Weighted Cross Sections= 1
Upstream XS Weight=0
Main XS Weight=1
Downstream XS Weight=0
Number of DS XS's Weighted with US Boundary= 1
Upstream Boundary Weight= 1
Weight of XSs Associated with US Boundary= 0
Number of US XS's Weighted with DS Boundary= 1
Downstream Boundary Weight= 0.5
Weight of XSs Associated with DS Boundary= 0.5
Percentile Method= 0
Sediment Output Level= 3
Mass or Volume Output= 0
Output Increment Type= 1
Profile and TS Output Increment= 1
Transport Output Increment 1
XS Output Flag= 0
XS Output Increment= 10
Read HDF5 Sediment Hotstart= 0
Sediment Hotstart Type= 0
Write Gradation File= 0
Read Gradation Hotstart= 0
Write HDF5 File= 1
Write Binary Output= 1
Write DSS Sediment File= 0
DSS Sediment Output Type= 1
SV Curve= 0
Specific Gage Flag= 0
Subcell Erosion Methods= 0
Subcell Deposition Methods= 0
Advection Scheme= 1
Matrix Solver= 0
Implicit Weighting Factor= 1
Maximum Outer Loop Convergence Iterations= 5
Convergence Maximum Absolute= 0.001
Convergence RMSE= 0.0001
Grain Fractions Max Abs Error= 0.001
Max Subgrid Regions= 1
Max Subgrid Length Scale= 3.402823E+38
Initial Layer Thickness= 3.402823E+38
Min Layer Thickness= 3.402823E+38
Max Layer Thickness= 3.402823E+38
Number of Layers= 5

--- PEARCYRN.f01 (steady flow) ---

Flow Title=Flow
Program Version=6.20
Number of Profiles= 1
Profile Names=P100yr
River Rch & RM=PEARCYRN,Main,17953
     349
River Rch & RM=PEARCYRN,Main,13663
     481
River Rch & RM=PEARCYRN,Main,12334
     538
River Rch & RM=PEARCYRN,Main,9505
     857
River Rch & RM=PEARCYRN,Main,3908
     986
Boundary for River Rch & Prof#=PEARCYRN,Main            , 1
Up Type= 0
Dn Type= 3
Dn Slope=0.001618
DSS Import GetInterval= 0
DSS Import GetPeak= 0
DSS Import FillOption= 0

--- PEARCYRN.g01 (geometry) ---

Geom Title=Geometry
Program Version=6.20

River Reach=PEARCYRN        ,Main
Reach XY= 30
     2292153.102      733284.637     2292424.369      733088.244
     2292347.112      732672.832     2292731.487      732463.457
     2292544.334      732151.652     2292864.039      730291.061
     2293074.543      730181.686     2292975.151      729899.134
     2293176.973      729824.047     2293247.344      729289.748
     2293058.542      728817.352     2293502.347      728375.599
     2293528.477      728086.599     2293882.079      727946.751
     2293828.906      727301.157     2294511.505      727069.751
     2295051.759      726545.245     2295499.111      726514.086
     2296132.777       725002.25     2296405.388      724976.211
     2296531.336      724617.286     2296255.826      724330.123
     2296385.248      724030.037     2296254.965      723963.114
     2296757.227      723809.203      2296735.83      722782.745
     2296397.119      722388.475     2296587.964      722265.295
     2296470.287      721977.605     2296609.473      721500.388

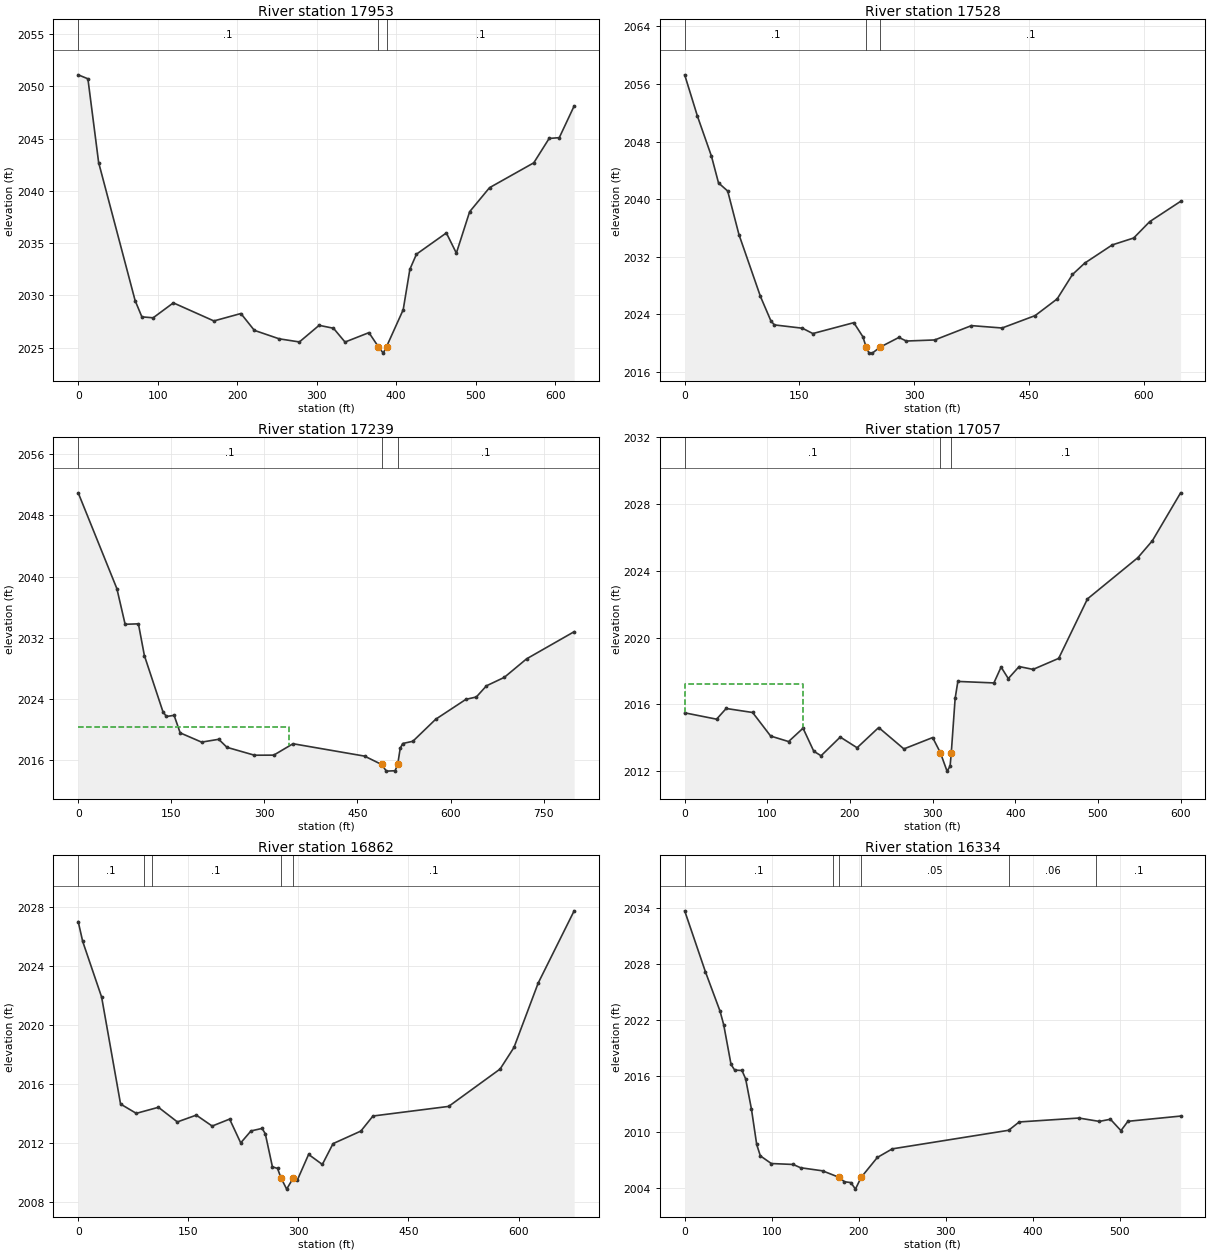
Type RM Length L Ch R = 1 ,17953   ,425.2,425.2,425.2
XS GIS Cut Line= 3
  2292438.441499733508.1014101912292232.19702442733284.195083593
2291926.28451474733191.784363959
#Sta/Elev= 30
       0  2051.1    12.2 2050.72    25.7 2042.71    71.6  2029.5    80.1 2027.94
    94.3 2027.85   119.7 2029.28   170.7 2027.55   204.7 2028.26   221.6 2026.65
   252.8 2025.84   278.3 2025.54   303.1 2027.13   321.2 2026.85   335.7 2025.53
   365.8 2026.43   377.5  2025.1   383.8 2024.47     388  2025.1   408.9 2028.62
   417.3 2032.49   425.6 2033.94   463.2 2035.97   475.8 2034.04   492.5    2038
   517.5  2040.3   573.2 2042.68   592.5 2045.01   605.3 2045.09     624 2048.12
#Mann= 3 ,-1,0
       0      .1       0   377.5    .045       0     388      .1       0
Bank Sta=377.5,388
XS Rating Curve= 0 ,0
Exp/Cntr(USF)=0,0
Exp/Cntr=0.3,0.1

Type RM Length L Ch R = 1 ,17528   ,289.2,289.2,289.2
XS GIS Cut Line= 3
2292634.84113364733202.818137095  2292381.253163733062.999799289
2292022.86942021733057.470981547
#Sta/Elev= 30
       0 2057.28    16.7 2051.53      35 2045.98    44.2 2042.27    56.2 2041.14
    70.9  2035.1      99  2026.5   112.7  2023.1   117.2 2022.55   153.8 2022.09
   167.5 2021.35     221 2022.86   232.8 2020.91  237.152019.473   240.6  2018.7
   245.1 2018.63  255.592019.474   279.9 2020.81   289.6 2020.31   326.7 2020.46
   374.7 2022.45   414.7 2022.12   457.9 2023.84   486.7 2026.16   506.7 2029.55
   522.7 2031.13   558.7 2033.66   586.7 2034.62   607.6 2036.89     648 2039.71
#Mann= 3 ,-1,0
       0      .1       0  237.15    .045       0  255.59      .1       0
Bank Sta=237.15,255.59
XS Rating Curve= 0 ,0
Exp/Cntr(USF)=0,0
Exp/Cntr=0.3,0.1

Type RM Length L Ch R = 1 ,17239   ,181.8,181.8,181.8
XS GIS Cut Line= 3
2292784.32181647733027.0827905632292367.95056717732827.543853198
2292038.04619073732898.047611067
#Sta/Elev= 30
       0 2050.96    62.3 2038.44    75.6 2033.78      97 2033.84   106.6  2029.7
   136.5 2022.36   142.1 2021.73   154.5 2021.88   164.3 2019.59   198.8 2018.38
   226.4 2018.75   239.7  2017.7     284 2016.67   315.1 2016.68   346.1 2018.17
   461.5 2016.55  488.742015.463   496.6 2014.59   510.6 2014.64  514.782015.464
   518.8 2017.56   522.8  2018.2   539.2 2018.49     576 2021.37   624.7 2023.97
   641.5 2024.28   657.8 2025.74   686.5 2026.84   722.4 2029.26   799.1 2032.81
#Mann= 3 ,-1,0
       0      .1       0  488.74    .045       0  514.78      .1       0
#XS Ineff= 2 , 0
          340.07 2020.36  571.62         2020.71
Permanent Ineff=
       F       F
Bank Sta=488.74,514.78
XS Rating Curve= 0 ,0
Exp/Cntr(USF)=0,0
Exp/Cntr=0.3,0.1

Type RM Length L Ch R = 1 ,17057   ,194.9,194.9,194.9
XS GIS Cut Line= 2
2292639.62188936732795.7698721112292088.74557838732557.998364142
#Sta/Elev= 30
       0  2015.5    38.6 2015.12    50.2 2015.76    82.2 2015.52     104 2014.11
   125.7 2013.78   143.2 2014.58   156.2  2013.2     165 2012.93   188.2 2014.05
   208.6 2013.41   234.7 2014.62   265.2 2013.34     300 2014.02   309.3 2013.12
   317.4 2012.01   321.1  2012.3  322.482013.067   327.2 2016.36   330.5 2017.38
   374.1 2017.29   382.8 2018.24   391.5 2017.55   404.6 2018.27   421.5  2018.1
   452.5 2018.76   487.3 2022.32   548.3 2024.79   565.8  2025.8     600 2028.67
#Mann= 3 ,-1,0
       0      .1       0   309.3    .045       0  322.48      .1       0
#XS Ineff= 2 , 0
          143.47 2017.23
Permanent Ineff=
       F       F
Bank Sta=309.3,322.48
XS Rating Curve= 0 ,0
Exp/Cntr(USF)=0,0
Exp/Cntr=0.3,0.1

Type RM Length L Ch R = 1 ,16862   ,528.1,528.1,528.1
XS GIS Cut Line= 4
2292753.84695169732722.1491875552292580.85134176732653.751660449
2292421.37450056732543.854666427 2292134.3951391 732471.48257258
#Sta/Elev= 30
       0 2027.01     6.1 2025.67    31.9  2021.9    57.7 2014.66    79.1 2014.03
   109.3 2014.44   135.1 2013.45   160.9 2013.91   182.5 2013.17   206.3 2013.64
   221.4 2012.03   235.4 2012.84   250.5 2013.01   254.9 2012.65   264.6 2010.41
   271.6  2010.3   276.1 2009.68     284  2008.9   293.3 2009.68   298.6 2009.52
   313.9 2011.25   332.6 2010.57   347.2 2011.98   385.1 2012.83   401.6 2013.85
   504.7  2014.5   574.8 2017.03   593.7 2018.49   626.7 2022.85   675.7 2027.74
#Mann= 5 ,-1,0
       0      .1       0      90     .06       0     100      .1       0
   276.1    .045       0   293.3      .1       0
Bank Sta=276.1,293.3
XS Rating Curve= 0 ,0
Exp/Cntr(USF)=0,0
Exp/Cntr=0.3,0.1

Type RM Length L Ch R = 1 ,16334   ,35.3,35.3,35.3
XS GIS Cut Line= 3
2292826.89012311732407.1818251482292576.80132161 732326.03599062
2292272.17187724732365.943778093
#Sta/Elev= 30
       0 2033.69    23.9 2027.15    40.7 2022.94    44.9 2021.48    53.3 2017.25
    57.5 2016.64    65.9  2016.6    70.1  2015.7    76.8 2012.45    82.8 2008.68
      87 2007.46    99.6 2006.64   124.8 2006.54   133.2 2006.19   158.5 2005.86
  177.482005.163   183.7 2004.69   191.1  2004.6   196.3  2003.9  202.922005.164
   221.5 2007.29   238.7 2008.21   372.5  2010.2   384.6 2011.09   453.2 2011.51
   476.7 2011.15   489.5 2011.38   501.6 2010.16   509.6 2011.16   570.2 2011.72
#Mann= 6 ,-1,0
       0      .1       0     170     .05       0  177.48    .045       0
  202.92     .05       0  372.92     .06       0  472.92      .1       0
Bank Sta=177.48,202.92
XS Rating Curve= 0 ,0
Exp/Cntr(USF)=0,0
Exp/Cntr=0.3,0.1

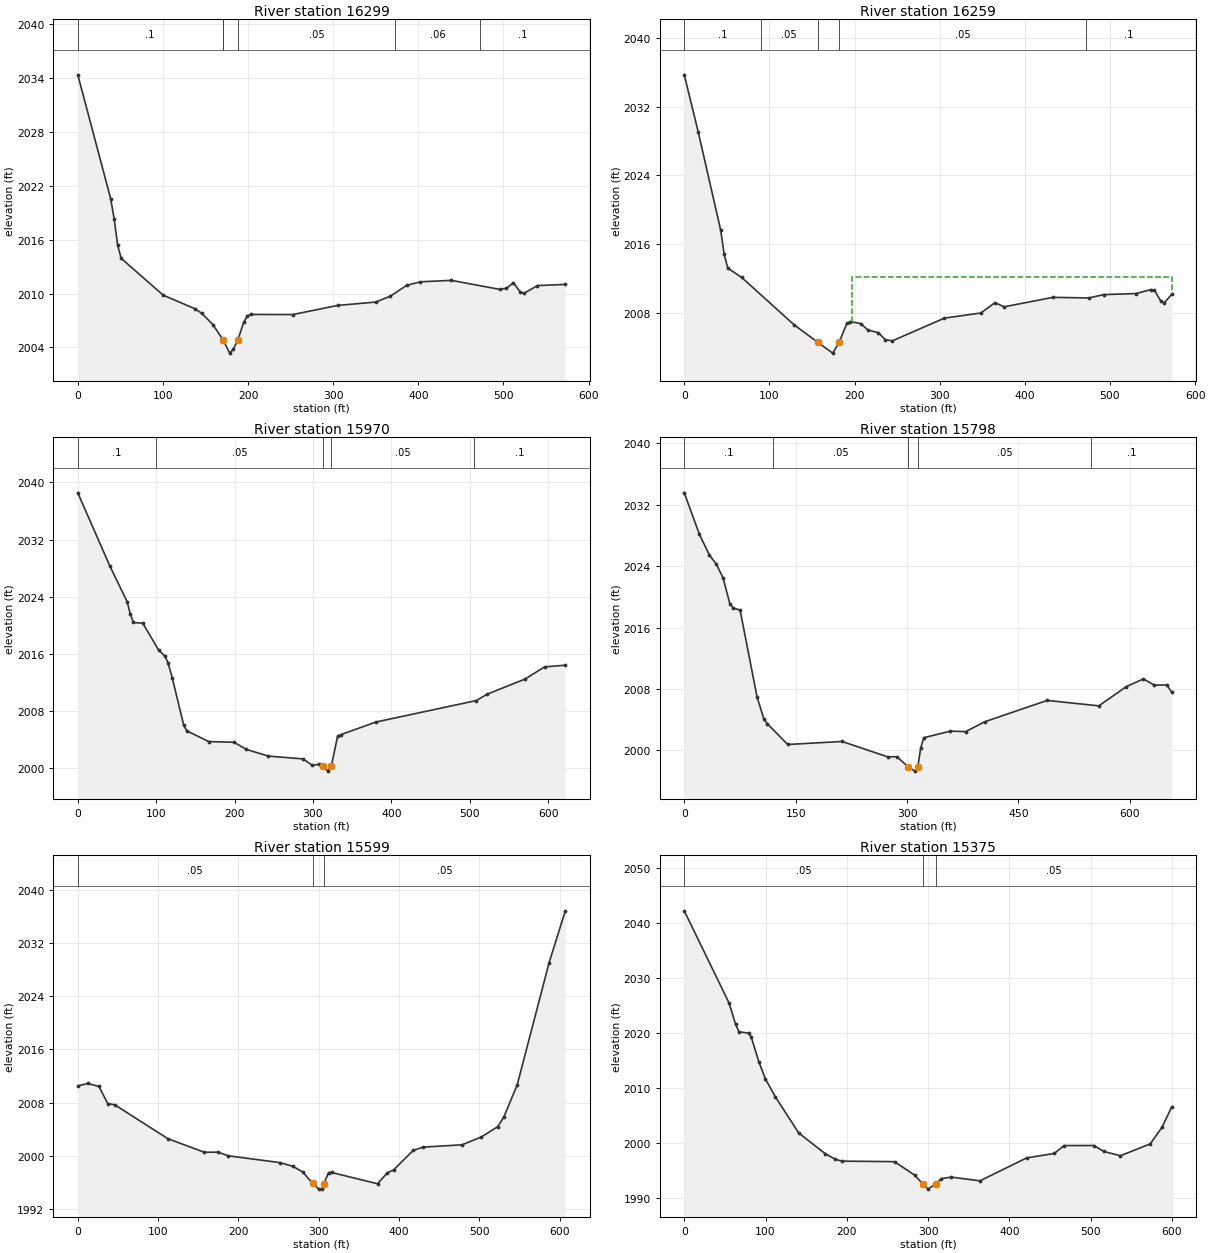
Type RM Length L Ch R = 1 ,16299   ,39.7,39.7,39.7
XS GIS Cut Line= 3
2292825.73877339 732354.818100122292560.83820662732291.449241476
2292263.81796685 732334.90373002
#Sta/Elev= 30
       0 2034.38    38.6 2020.58    42.7 2018.34    46.8 2015.39      51 2013.92
   100.3 2009.82   137.3 2008.32   145.6  2007.8   158.6 2006.55  170.482004.852
   178.5 2003.36   182.6 2003.78  188.092004.854   194.9  2006.8     199 2007.49
   203.1 2007.67   252.5 2007.66   305.4 2008.68   349.9 2009.05   367.2 2009.71
   386.2 2010.91   402.4 2011.31   438.8 2011.47   495.4 2010.47   503.5 2010.58
   511.6 2011.21   519.6 2010.18   523.7 2010.01   539.9 2010.89   572.6 2011.02
#Mann= 6 ,-1,0
       0      .1       0     170     .05       0  170.48    .045       0
  188.09     .05       0  372.37     .06       0  472.37      .1       0
Bank Sta=170.48,188.09
XS Rating Curve= 0 ,0
Exp/Cntr(USF)=0,0
Exp/Cntr=0.3,0.1

Type RM Length L Ch R = 1 ,16259   ,289.5,289.5,289.5
XS GIS Cut Line= 3
2292829.82627365732315.1521133042292564.92570689 732251.78325466
2292267.90546711732295.237743204
#Sta/Elev= 30
       0 2035.71    16.3 2029.11    42.8 2017.63    46.9 2014.81    51.1 2013.22
    67.5 2012.13   129.2 2006.61  156.652004.598   174.4 2003.33  182.022004.598
   190.9 2006.78     195 2006.99   207.3 2006.77   215.6 2006.02   227.9 2005.71
   236.1  2004.9   244.4 2004.76   305.5  2007.4   348.3    2008   364.9  2009.2
   375.8 2008.72     433 2009.82   475.2 2009.75   492.9 2010.14   530.7 2010.26
     548 2010.72   552.1 2010.65   559.9 2009.37   563.5 2009.16   572.6 2010.18
#Mann= 5 ,-1,0
       0      .1       0      90     .05       0  156.65    .045       0
  182.02     .05       0  472.37      .1       0
#XS Ineff= 2 , 0
                           197.4         2012.14
Permanent Ineff=
       F       F
Bank Sta=156.65,182.02
XS Rating Curve= 0 ,0
Exp/Cntr(USF)=0,0
Exp/Cntr=0.3,0.1

Type RM Length L Ch R = 1 ,15970   ,171.8,171.8,171.8
XS GIS Cut Line= 3
2292863.03559798732153.3341935642292498.31600625732133.148351167
2292250.69511053 732200.51527568
#Sta/Elev= 30
       0 2038.53    40.8 2028.32      63 2023.29      67 2021.56      71  2020.4
      83 2020.29     103 2016.55     111 2015.72     115  2014.8   120.5 2012.66
   135.1 2006.04   139.1 2005.24   167.1 2003.74   199.2 2003.65   215.2 2002.64
   243.2 2001.71   287.3 2001.32   299.3 2000.42   307.3 2000.56   312.4 2000.27
   319.3 1999.61   323.4 2000.29   331.4  2004.5   335.4  2004.7   380.1 2006.47
   508.4 2009.48     522 2010.36   570.6 2012.49   595.5 2014.19   621.9 2014.42
#Mann= 5 ,-1,0
       0      .1       0     100     .05       0   312.4    .045       0
   323.4     .05       0  505.28      .1       0
Bank Sta=312.4,323.4
XS Rating Curve= 0 ,0
Exp/Cntr(USF)=0,0
Exp/Cntr=0.3,0.1

Type RM Length L Ch R = 1 ,15798   ,199.1,199.1,199.1
XS GIS Cut Line= 4
2292865.82450525732106.093737314  2292671.596986731997.835775764
2292507.61801483731977.1394007622292275.18180327732112.461852699
#Sta/Elev= 30
       0 2033.55    20.2  2028.2    33.9 2025.43    43.1 2024.27    52.3 2022.48
    61.4 2019.11      66 2018.55    75.2 2018.28    98.1 2006.94   107.2 2004.12
   111.8 2003.49   139.3 2000.78   212.5 2001.17   274.2 1999.16   286.3 1999.19
   301.51997.884   310.5 1997.31   314.5 1997.85   318.5 2000.34   322.6 2001.66
   358.5 2002.52     379 2002.45   404.8 2003.74   488.8 2006.52   558.3 2005.81
   595.3 2008.31   618.4 2009.32     633 2008.51   650.1 2008.53   656.6 2007.57
#Mann= 5 ,-1,0
       0      .1       0     120     .05       0   301.5    .045       0
   314.5     .05       0  547.64      .1       0
Bank Sta=301.5,314.5
XS Rating Curve= 0 ,0
Exp/Cntr(USF)=0,0
Exp/Cntr=0.3,0.1

Type RM Length L Ch R = 1 ,15599   ,224.2,224.2,224.2
XS GIS Cut Line= 4
2292839.16230453731967.5466617762292676.37307254731803.608256512
2292504.43395714731774.9517372792292304.89188076731745.533224603
#Sta/Elev= 30
       0 2010.53    12.3 2010.89    26.4 2010.45    37.2 2007.88    46.2 2007.68
   112.1  2002.6   157.5 2000.56   174.5 2000.58   187.6 2000.02   251.5 1999.01
   267.7 1998.45   279.9 1997.62   292.4 1995.88   300.2 1995.02   304.2 1995.06
   306.2 1995.81   312.3 1997.51   315.9 1997.52   373.2 1995.83   385.3 1997.45
   393.4 1997.93   417.7 2000.84   429.9 2001.33   478.4 2001.68   502.3 2002.84
   522.9 2004.41   530.5 2005.87   547.1 2010.68   586.8 2029.03     607 2036.83
#Mann= 3 ,-1,0
       0     .05       0   292.4    .045       0   306.2     .05       0
Bank Sta=292.4,306.2
XS Rating Curve= 0 ,0
Exp/Cntr(USF)=0,0
Exp/Cntr=0.3,0.1

Type RM Length L Ch R = 1 ,15375   ,149.5,149.5,149.5
XS GIS Cut Line= 2
2292982.09435029731644.5527878482292394.20563573731524.607553296
#Sta/Elev= 30
       0 2042.25      55 2025.51    63.2 2021.61    67.3 2020.23    79.5 2019.97
    82.5 2019.23    91.8 2014.76    99.9 2011.64   112.2 2008.36   140.8 2001.82
   173.4 1998.04   185.7 1997.03   193.8 1996.68   258.8 1996.58   283.6 1994.11
   293.71992.515     300 1991.58  309.291992.514   316.4  1993.5   328.6 1993.77
   363.9 1993.09   421.5 1997.27   455.4 1998.07   467.4 1999.51   504.1 1999.52
   516.3 1998.44   536.8 1997.66   573.5 1999.82     588 2002.83     600 2006.57
#Mann= 3 ,-1,0
       0     .05       0   293.7    .045       0  309.29     .05       0
Bank Sta=293.7,309.29
XS Rating Curve= 0 ,0
Exp/Cntr(USF)=0,0
Exp/Cntr=0.3,0.1

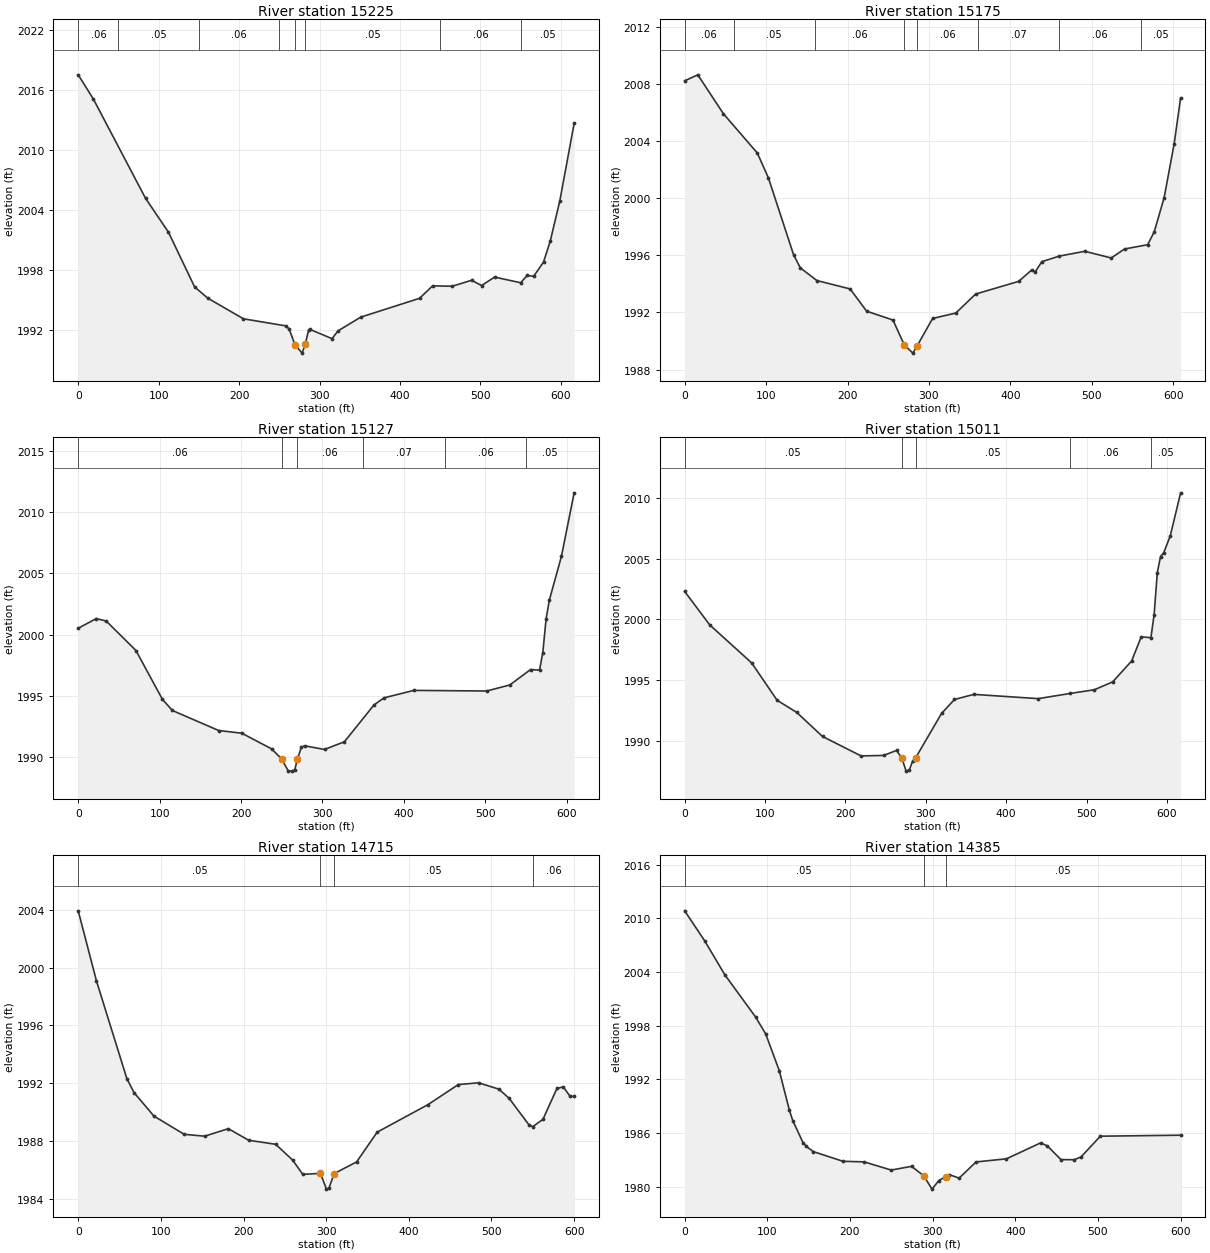
Type RM Length L Ch R = 1 ,15225   ,50.7,50.7,50.7
XS GIS Cut Line= 2
2293002.73898604731489.9785737872292394.58396674731388.088727622
#Sta/Elev= 30
       0 2017.55    18.8 2015.13    83.7 2005.18   112.1  2001.8   144.6 1996.32
   160.8 1995.19   205.4 1993.11   258.1  1992.4   262.2 1992.09   269.61990.491
   278.4 1989.67   282.4 1990.61   286.5 1991.99   287.8 1992.06   315.6 1991.12
     323  1991.9   351.4 1993.28   424.4 1995.16   440.6 1996.41   464.8 1996.37
   489.2 1996.97   501.5 1996.44   517.7 1997.29   550.1 1996.72   558.2 1997.45
   566.3 1997.37   578.5 1998.79   586.8 2000.87   598.8 2004.93   616.6 2012.69
#Mann= 8 ,-1,0
       0     .06       0      50     .05       0     150     .06       0
     250     .05       0   269.6    .045       0   282.4     .05       0
     450     .06       0     550     .05       0
Bank Sta=269.6,282.4
XS Rating Curve= 0 ,0
Exp/Cntr(USF)=0,0
Exp/Cntr=0.3,0.1

Type RM Length L Ch R = 1 ,15175   ,47.3,47.3,47.3
XS GIS Cut Line= 2
2293016.01701762731444.5125434242292416.33056977731338.033027206
#Sta/Elev= 30
       0 2008.24    16.1 2008.66    47.6 2005.93    89.2 2003.18   102.8 2001.44
   133.8 1996.04     142 1995.13   162.3 1994.24   203.2 1993.65   223.5 1992.09
   255.8 1991.47   269.61989.739   280.2 1989.15   285.6 1989.67   304.5 1991.58
     333 1991.96   357.3 1993.29   410.2 1994.18   426.4 1994.99   430.5 1994.84
   438.6 1995.56     460 1995.95   491.4 1996.29   523.9 1995.82   540.2 1996.45
   568.6 1996.75   576.7 1997.65   588.9 2000.06   601.1  2003.8   609.1 2007.04
#Mann= 8 ,-1,0
       0     .06       0      60     .05       0     160     .06       0
   269.6    .045       0   285.6     .06       0     360     .07       0
     460     .06       0     560     .05       0
Bank Sta=269.6,285.6
XS Rating Curve= 0 ,0
Exp/Cntr(USF)=0,0
Exp/Cntr=0.3,0.1

Type RM Length L Ch R = 1 ,15127   ,116,116,116
XS GIS Cut Line= 2
2293010.01023403731395.4484147472292410.32378618731288.968898529
#Sta/Elev= 30
       0 2000.52    22.2 2001.31    34.4 2001.11    70.9  1998.7   103.4 1994.71
   115.6  1993.8   172.5 1992.16   200.9 1991.94   237.5 1990.66   249.7 1989.85
   257.8 1988.88   262.3 1988.84   265.9 1988.94   269.2 1989.81   274.1  1990.8
   278.1 1990.91   302.5 1990.61   326.9 1991.24   363.4 1994.26   375.6 1994.83
   412.2 1995.44   501.6 1995.39     530 1995.88   555.5 1997.14   566.6  1997.1
   570.6 1998.53   574.7 2001.31   578.7 2002.84   593.5  2006.4   609.1 2011.59
#Mann= 6 ,-1,0
       0     .06       0   249.7    .045       0   269.2     .06       0
     350     .07       0     450     .06       0     550     .05       0
Bank Sta=249.7,269.2
XS Rating Curve= 0 ,0
Exp/Cntr(USF)=0,0
Exp/Cntr=0.3,0.1

Type RM Length L Ch R = 1 ,15011   ,296.5,296.5,296.5
XS GIS Cut Line= 2
 2293039.3556495731255.9503333772292423.24048598731220.925698758
#Sta/Elev= 30
       0 2002.29    31.2 1999.54    83.3 1996.42   115.1 1993.34   139.4 1992.35
   171.5 1990.37   219.5 1988.77   247.6 1988.81   263.6 1989.22   270.1 1988.61
   275.6 1987.52   279.6 1987.63   283.6 1988.34   287.6 1988.64   319.7 1992.27
   335.7 1993.41   359.8 1993.83   439.9 1993.48     480 1993.91   509.8 1994.21
   532.6 1994.86   556.1 1996.57   568.1 1998.56   580.1 1998.49   584.1 2000.36
   588.1 2003.84   592.1 2005.16   596.1 2005.48   604.2 2006.86   617.1  2010.4
#Mann= 5 ,-1,0
       0     .05       0   270.1    .045       0   287.6     .05       0
     480     .06       0     580     .05       0
Bank Sta=270.1,287.6
XS Rating Curve= 0 ,0
Exp/Cntr(USF)=0,0
Exp/Cntr=0.3,0.1

Type RM Length L Ch R = 1 ,14715   ,330,330,330
XS GIS Cut Line= 2
2293101.73006968 731031.927208912292515.23201273730905.356954896
#Sta/Elev= 30
       0 2003.92    22.1 1999.07    58.9 1992.31    67.6 1991.35    91.6 1989.73
   128.2 1988.47     153 1988.34   181.6 1988.86   206.2 1988.06   238.9 1987.78
   259.4 1986.69   271.7  1985.7   293.1 1985.77   300.3 1984.68   303.2 1984.73
   309.71985.756   336.8 1986.56   361.7 1988.62   423.1 1990.52   459.9 1991.91
   484.5 1992.03     509 1991.59   521.3 1990.96   545.5 1989.11   549.9    1989
   562.2  1989.5   579.2 1991.64   586.8 1991.75   594.9 1991.11     600 1991.09
#Mann= 4 ,-1,0
       0     .05       0   293.1    .045       0   309.7     .05       0
     550     .06       0
Bank Sta=293.1,309.7
XS Rating Curve= 0 ,0
Exp/Cntr(USF)=0,0
Exp/Cntr=0.3,0.1

Type RM Length L Ch R = 1 ,14385   ,279.1,279.1,279.1
XS GIS Cut Line= 2
2293195.62914849730729.1532210882292611.09224883730593.814339264
#Sta/Elev= 30
       0 2010.85    24.1 2007.51    48.7 2003.68    85.7 1998.99      98 1997.09
   114.4 1992.99   126.7 1988.55   130.8 1987.39   143.1 1984.94   147.2 1984.51
   155.5 1983.93   191.6 1982.84     217 1982.78   249.9 1981.86   274.5 1982.28
  289.381981.202   299.2 1979.73   307.4 1980.68   315.6 1981.13   319.9 1981.36
     332 1980.96   352.5 1982.77   389.3 1983.12   430.6  1984.9   438.8 1984.56
   455.2 1983.03   471.6 1983.02   479.6 1983.34   502.9 1985.65     600 1985.76
#Mann= 3 ,-1,0
       0     .05       0  289.38    .045       0   315.6     .05       0
Bank Sta=289.38,315.6
XS Rating Curve= 0 ,0
Exp/Cntr(USF)=0,0
Exp/Cntr=0.3,0.1

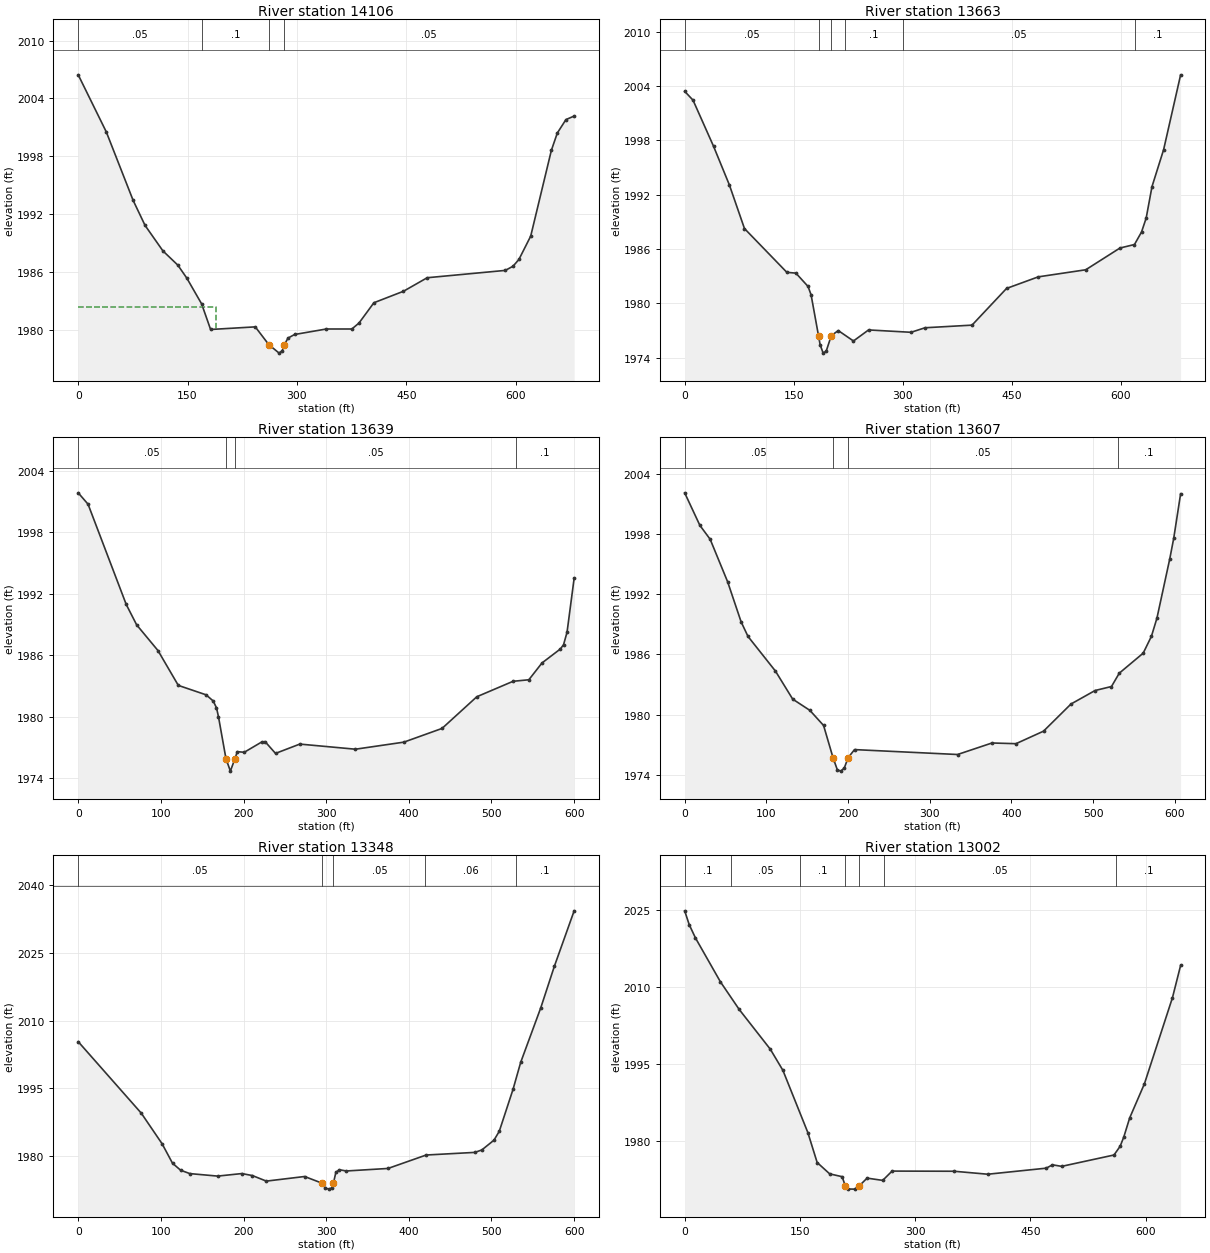
Type RM Length L Ch R = 1 ,14106   ,442.1,442.1,442.1
XS GIS Cut Line= 3
 2293221.8856932730446.7912890312292921.33855347730383.857000264
2292553.46563872730446.715371761
#Sta/Elev= 30
       0 2006.45    38.5 2000.54    75.3 1993.45    91.7 1990.85   116.2 1988.21
   136.6 1986.74   148.9  1985.4   169.3 1982.72   181.6 1980.07   242.9 1980.34
  261.431978.502   275.6 1977.62   279.9 1977.88  282.821978.501   287.8 1979.18
   296.8 1979.55   340.4 1980.12   375.4 1980.12   385.2 1980.74   405.6 1982.84
   446.2 1984.03   478.7 1985.43   585.8 1986.19   596.4 1986.62   604.5 1987.32
   620.7 1989.74   649.1 1998.64   657.2 2000.42     669 2001.81   680.3 2002.18
#Mann= 4 ,-1,0
       0     .05       0     170      .1       0  261.43    .045       0
  282.82     .05       0
#XS Ineff= 2 , 0
          189.65 1982.44
Permanent Ineff=
       F       F
Bank Sta=261.43,282.82
XS Rating Curve= 0 ,0
Exp/Cntr(USF)=0,0
Exp/Cntr=0.3,0.1

Type RM Length L Ch R = 1 ,13663   ,24.4,24.4,24.4
XS GIS Cut Line= 3
2293263.21526615 730212.253514132292878.77024683730100.511709206
2292596.75521535730088.539372964
#Sta/Elev= 30
       0 2003.41    11.5 2002.43    39.7 1997.35    61.5 1993.08    82.3 1988.26
   140.6 1983.43   153.1 1983.34   169.8 1981.87     174 1980.94  184.241976.412
   186.4 1975.45   190.6 1974.51   194.8 1974.73   201.8 1976.44   211.4    1977
   232.3 1975.85   253.1 1977.07   311.5 1976.81   330.9 1977.31   395.5  1977.6
     443 1981.65   486.7 1982.93     552 1983.71   599.1 1986.11   619.1  1986.5
   628.8 1987.88   635.2 1989.42   643.2 1992.89   659.2 1996.97   682.6 2005.23
#Mann= 6 ,-1,0
       0     .05       0  184.24    .045       0   201.8     .05       0
     220      .1       0     300     .05       0  620.36      .1       0
Bank Sta=184.24,201.8
XS Rating Curve= 0 ,0
Exp/Cntr(USF)=0,0
Exp/Cntr=0.3,0.1

Type RM Length L Ch R = 1 ,13639   ,31.8,31.8,31.8
XS GIS Cut Line= 2
2293259.53691844730191.0446043642292687.95853862730008.566781831
#Sta/Elev= 30
       0 2001.87    11.9 2000.76    58.1 1990.97    70.7 1988.98    96.5 1986.47
   121.1 1983.07   154.7 1982.15   163.3 1981.55   167.3 1980.88   169.7 1980.01
  178.761975.915   184.1  1974.7  189.611975.914   192.5  1976.6   200.9 1976.54
   221.9 1977.54   226.1 1977.58   238.7 1976.43   268.1 1977.34   335.4 1976.84
     394 1977.53   440.2 1978.87   482.2 1981.96   526.1 1983.47   545.2 1983.62
   561.1 1985.26   583.4 1986.63   587.2 1987.05   591.4 1988.26     600 1993.54
#Mann= 4 ,-1,0
       0     .05       0  178.76    .045       0  189.61     .05       0
     530      .1       0
Bank Sta=178.76,189.61
XS Rating Curve= 0 ,0
Exp/Cntr(USF)=0,0
Exp/Cntr=0.3,0.1

Type RM Length L Ch R = 1 ,13607   ,259,259,259
XS GIS Cut Line= 2
2293265.87578531730161.7036499982292688.54312654729974.137048874
#Sta/Elev= 30
       0 2002.14    18.6 1998.89    31.2  1997.5    52.6 1993.25    69.1 1989.25
    77.5  1987.8   111.1 1984.34   132.2 1981.54   153.2 1980.42     170 1978.91
  181.551975.696   186.8 1974.49     191 1974.35   195.3 1974.65  200.051975.694
   207.9  1976.5     334 1976.01   376.1 1977.16   405.5 1977.09   439.2 1978.34
   472.8 1981.05   502.3  1982.4   522.4  1982.8   531.9 1984.13   561.2 1986.13
   571.3 1987.82     578 1989.62   593.7 1995.54   598.6 1997.62     607 2002.05
#Mann= 4 ,-1,0
       0     .05       0  181.55    .045       0  200.05     .05       0
     530      .1       0
Bank Sta=181.55,200.05
XS Rating Curve= 0 ,0
Exp/Cntr(USF)=0,0
Exp/Cntr=0.3,0.1

Type RM Length L Ch R = 1 ,13348   ,346.1,346.1,346.1
XS GIS Cut Line= 2
2293260.72963104 730013.973741832292689.86419111729829.277641438
#Sta/Elev= 30
       0 2005.34    76.3 1989.54   101.5 1982.77   114.1 1978.47   123.9 1976.93
   135.1 1976.18   168.7 1975.63     198 1976.19   210.7 1975.75   227.6 1974.52
   273.9 1975.54  294.711974.086   299.1 1972.99   303.3 1972.75   307.5 1973.09
  308.771974.084   311.7 1976.44   315.9 1977.04   324.3 1976.76   374.8 1977.32
     421 1980.29   479.9 1980.87   488.3 1981.41     503 1983.57   509.4 1985.53
   526.1 1994.83   535.3 2000.76   559.7 2012.87     576 2021.97     600 2034.26
#Mann= 5 ,-1,0
       0     .05       0  294.71    .045       0  308.77     .05       0
     420     .06       0     530      .1       0
Bank Sta=294.71,308.77
XS Rating Curve= 0 ,0
Exp/Cntr(USF)=0,0
Exp/Cntr=0.3,0.1

Type RM Length L Ch R = 1 ,13002   ,195.6,195.6,195.6
XS GIS Cut Line= 3
2293409.96643261729762.6366212772293113.25092655 729710.04858774
2292769.49622135729694.628108908
#Sta/Elev= 30
       0 2024.85     5.9 2022.16      14 2019.58    46.5 2011.04    70.9 2005.67
   111.5 1997.91   127.8 1993.82   160.3  1981.7   172.4 1975.88   188.7 1973.67
   204.9 1973.12     209 1971.35   213.1 1970.72   221.2  1970.7  227.151971.337
   237.4 1972.84   257.7  1972.4   269.9 1974.21   350.5 1974.18   394.5  1973.6
   470.6 1974.78   478.6 1975.43   490.6 1975.13   558.7 1977.34   566.7 1979.04
   571.5 1980.86   579.1 1984.55   598.3  1991.2   634.8 2007.96   645.4 2014.23
#Mann= 7 ,-1,0
       0      .1       0      60     .05       0     150      .1       0
     209    .045       0  227.15      .1       0     260     .05       0
  561.34      .1       0
Bank Sta=209,227.15
XS Rating Curve= 0 ,0
Exp/Cntr(USF)=0,0
Exp/Cntr=0.3,0.1

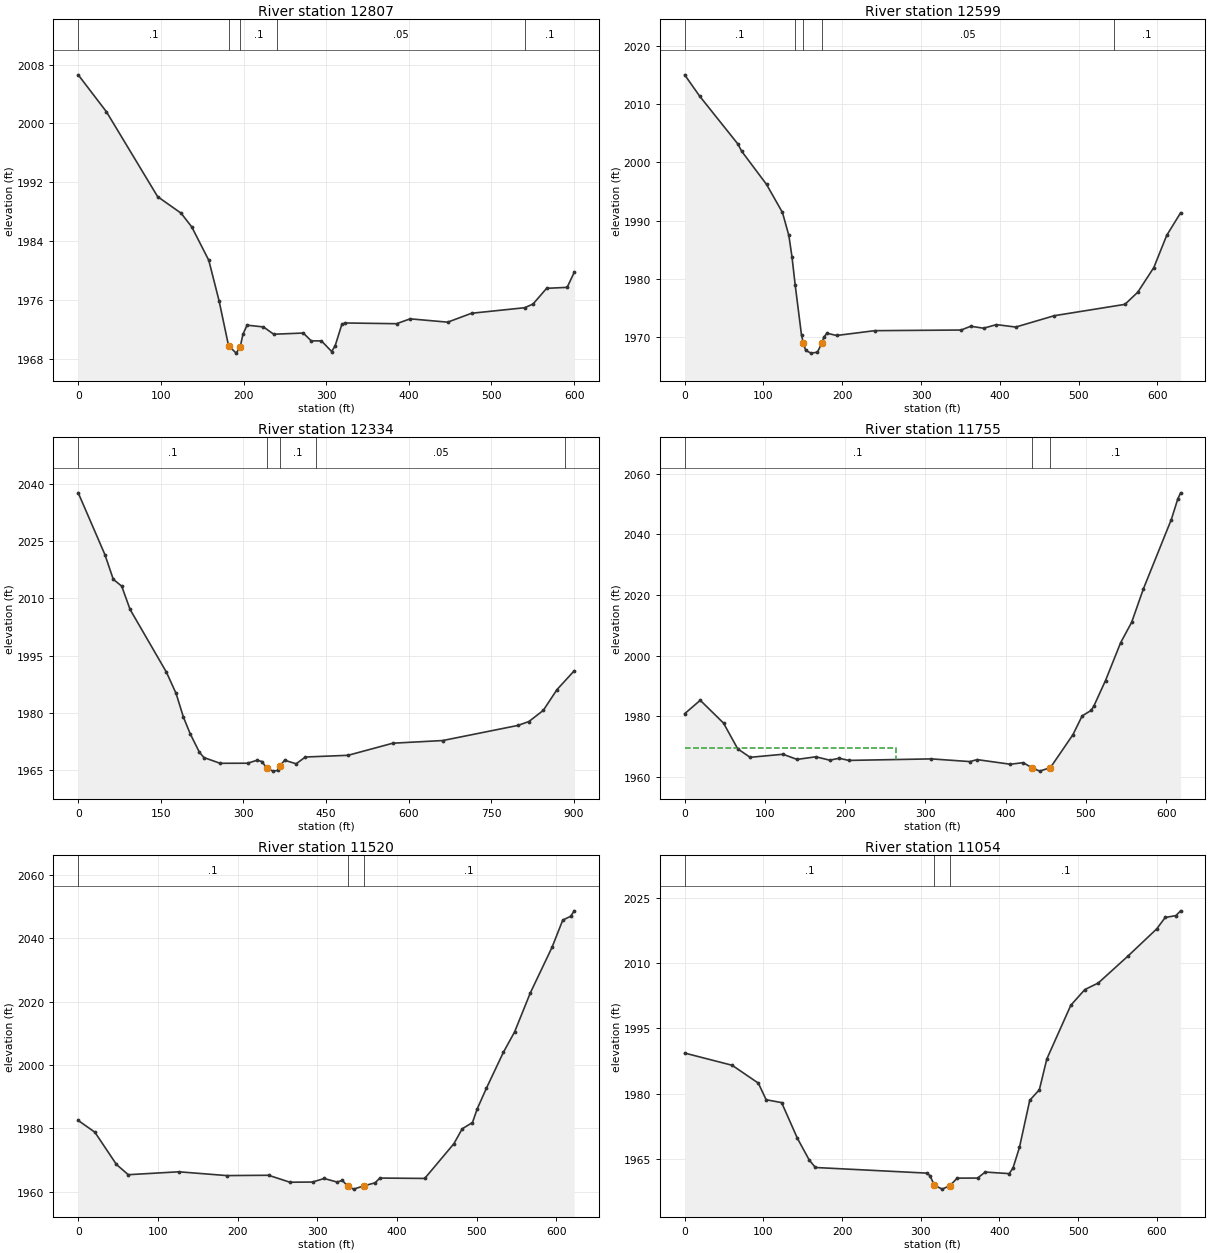
Type RM Length L Ch R = 1 ,12807   ,207.3,207.3,207.3
XS GIS Cut Line= 2
2293385.30424559729580.4560798262292803.90245364729432.226675466
#Sta/Elev= 30
       0 2006.61    34.2 2001.58    96.1 1990.05   124.5  1987.8   137.4 1985.93
     158 1981.39   170.4  1975.9  181.871969.791   191.1 1968.78     1961969.636
   199.3 1971.35   204.3 1972.58   224.1 1972.34   236.5 1971.35   272.3 1971.51
   281.9 1970.45   294.3 1970.44   306.6    1969   310.8 1969.76     319 1972.71
   323.1 1972.88   385.1 1972.78   401.6 1973.44     447 1972.99   475.9  1974.2
     540 1974.95   550.2 1975.45   566.7 1977.59   591.5 1977.72     600 1979.74
#Mann= 5 ,-1,0
       0      .1       0  181.87    .045       0     196      .1       0
     240     .05       0     540      .1       0
Bank Sta=181.87,196
XS Rating Curve= 0 ,0
Exp/Cntr(USF)=0,0
Exp/Cntr=0.3,0.1

Type RM Length L Ch R = 1 ,12599   ,264.7,264.7,264.7
XS GIS Cut Line= 3
2293394.99935836729356.1631628222293103.54491316729314.528542091
2292774.76587671729379.497404244
#Sta/Elev= 30
       0 2015.04      19 2011.38    67.5 2003.16    72.3 2001.92   103.9 1996.21
   124.1 1991.39   132.2 1987.45   136.2 1983.77   140.2    1979   148.3  1970.3
   150.7 1968.92   153.6 1967.69   160.4 1967.22   168.5 1967.38   174.2 1968.99
   176.6 1969.97   180.6 1970.64   192.8 1970.25   241.2 1971.08   350.9 1971.19
   363.1 1971.84   379.4  1971.5   395.7 1972.12   420.2  1971.7   469.1 1973.65
   558.8  1975.6   575.1 1977.69   595.5 1981.93   611.8 1987.44   629.5 1991.34
#Mann= 5 ,-1,0
       0      .1       0     140     .05       0   150.7    .045       0
   174.2     .05       0  544.41      .1       0
Bank Sta=150.7,174.2
XS Rating Curve= 0 ,0
Exp/Cntr(USF)=0,0
Exp/Cntr=0.3,0.1

Type RM Length L Ch R = 1 ,12334   ,579.1,579.1,579.1
XS GIS Cut Line= 4
2293530.30324193729144.7079861472293379.99492874729026.733905804
2293118.47468059729106.8032607262292749.89071757729340.311782332
#Sta/Elev= 30
       0 2037.57    48.5 2021.41    63.7 2014.96      79 2013.17    94.2 2007.08
   160.3 1990.66   177.8  1985.1   191.1 1978.93   203.4 1974.58   220.2 1969.72
   228.5 1968.34   257.8 1966.85   307.7 1966.87   324.8 1967.64   333.8 1967.31
   342.41965.592     354  1964.8   362.4 1964.99   366.31966.157     375 1967.65
   395.9 1966.72   412.6 1968.49   490.2 1968.94   571.5  1972.1   662.2  1972.8
   798.8 1976.75   818.7 1977.77   844.8 1980.68   869.8 1986.13   900.9 1991.02
#Mann= 5 ,-1,0
       0      .1       0   342.4    .045       0   366.3      .1       0
  431.08     .05       0  884.58      .1       0
Bank Sta=342.4,366.3
XS Rating Curve= 0 ,0
Exp/Cntr(USF)=0,0
Exp/Cntr=0.3,0.1

Type RM Length L Ch R = 1 ,11755   ,235.4,235.4,235.4
XS GIS Cut Line= 3
2293443.48183566728948.2791301092293461.48298999728955.471866948
2292938.91874283728663.516407397
#Sta/Elev= 30
       0  1980.8    19.4 1985.23    48.4  1977.7    66.1  1969.2    81.5  1966.4
   122.5 1967.41     140 1965.71   163.5 1966.57   180.8 1965.45   192.5 1966.09
   204.5 1965.38   307.5 1965.88   355.4 1964.99   364.5 1965.64   405.8 1964.11
   421.8 1964.64  432.511962.993   442.4 1961.84  455.721962.993   483.7 1973.83
   495.3 1980.07   506.6  1981.9     510 1983.39   524.4 1991.75   543.2 2004.21
     557 2010.99   571.7 2022.08   606.4  2044.9   614.6 2051.79     618 2053.71
#Mann= 3 ,-1,0
       0      .1       0  432.51    .045       0  455.72      .1       0
#XS Ineff= 2 , 0
          263.22 1969.57
Permanent Ineff=
       F       F
Bank Sta=432.51,455.72
XS Rating Curve= 0 ,0
Exp/Cntr(USF)=0,0
Exp/Cntr=0.3,0.1

Type RM Length L Ch R = 1 ,11520   ,466.2,466.2,466.2
XS GIS Cut Line= 3
2293474.84988967 728902.191130642293397.15181821728734.594242028
2293024.52863065728505.228048666
#Sta/Elev= 30
       0  1982.5    20.9 1978.78      48 1968.58    62.8 1965.35   126.3 1966.27
   186.5 1965.07   238.8 1965.17   265.7 1962.97     294 1963.03   308.6 1964.15
   324.8 1963.03   331.5 1963.54 338.3991961.629   345.6 1960.79358.86321961.861
   372.5 1962.78   378.5 1964.29   434.8 1964.17   471.4 1975.15   481.8 1979.85
   494.7 1981.84   500.6 1986.11   512.1 1992.63   533.5 2004.03   547.6 2010.49
   567.3 2022.81   594.5 2037.19     608 2045.81     618 2047.03   622.3 2048.74
#Mann= 3 ,-1,0
       0      .1       0 338.399    .045       0358.8632      .1       0
Bank Sta=338.399,358.8632
XS Rating Curve= 0 ,0
Exp/Cntr(USF)=0,0
Exp/Cntr=0.3,0.1

Type RM Length L Ch R = 1 ,11054   ,493.9,493.9,493.9
XS GIS Cut Line= 3
 2293759.4701648728570.235246941 2293452.9613952728343.927203074
2293224.03097395728245.408954786
#Sta/Elev= 30
       0 1989.31    60.3  1986.5    93.6 1982.39   103.5 1978.57   123.2  1977.9
   143.3 1969.67   158.2 1964.71   166.1 1962.97   307.4 1961.68   311.6 1961.12
   317.3 1958.88   327.3 1957.99   337.2 1958.82   346.3 1960.52   372.2 1960.54
   381.9 1961.92   412.3 1961.56   417.2 1962.84   425.4 1967.59   438.5 1978.44
   450.7 1980.87   460.2 1987.96   490.7 2000.33   508.5 2003.93   525.6 2005.44
   563.3 2011.64   599.9 2017.91   610.6 2020.52   624.2 2020.95   630.2 2022.05
#Mann= 3 ,-1,0
       0      .1       0   317.3    .045       0   337.2      .1       0
Bank Sta=317.3,337.2
XS Rating Curve= 0 ,0
Exp/Cntr(USF)=0,0
Exp/Cntr=0.3,0.1