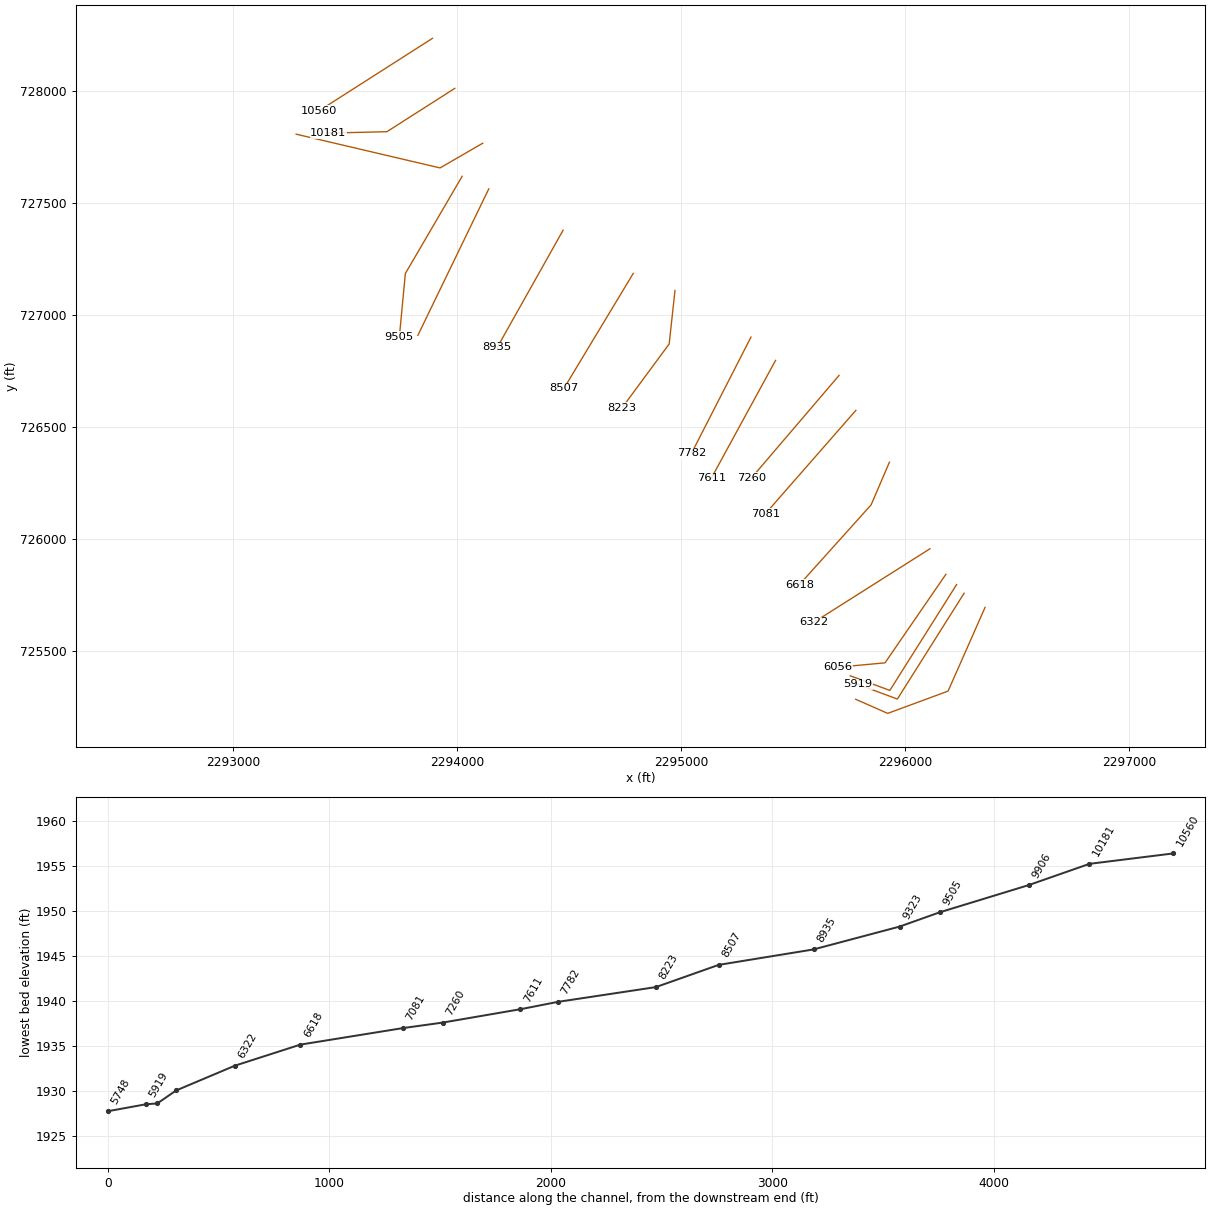
HEC-RAS study PEARCYRN.prj: PEARCYRN

--- PEARCYRN.g01 (geometry) --- (continued)

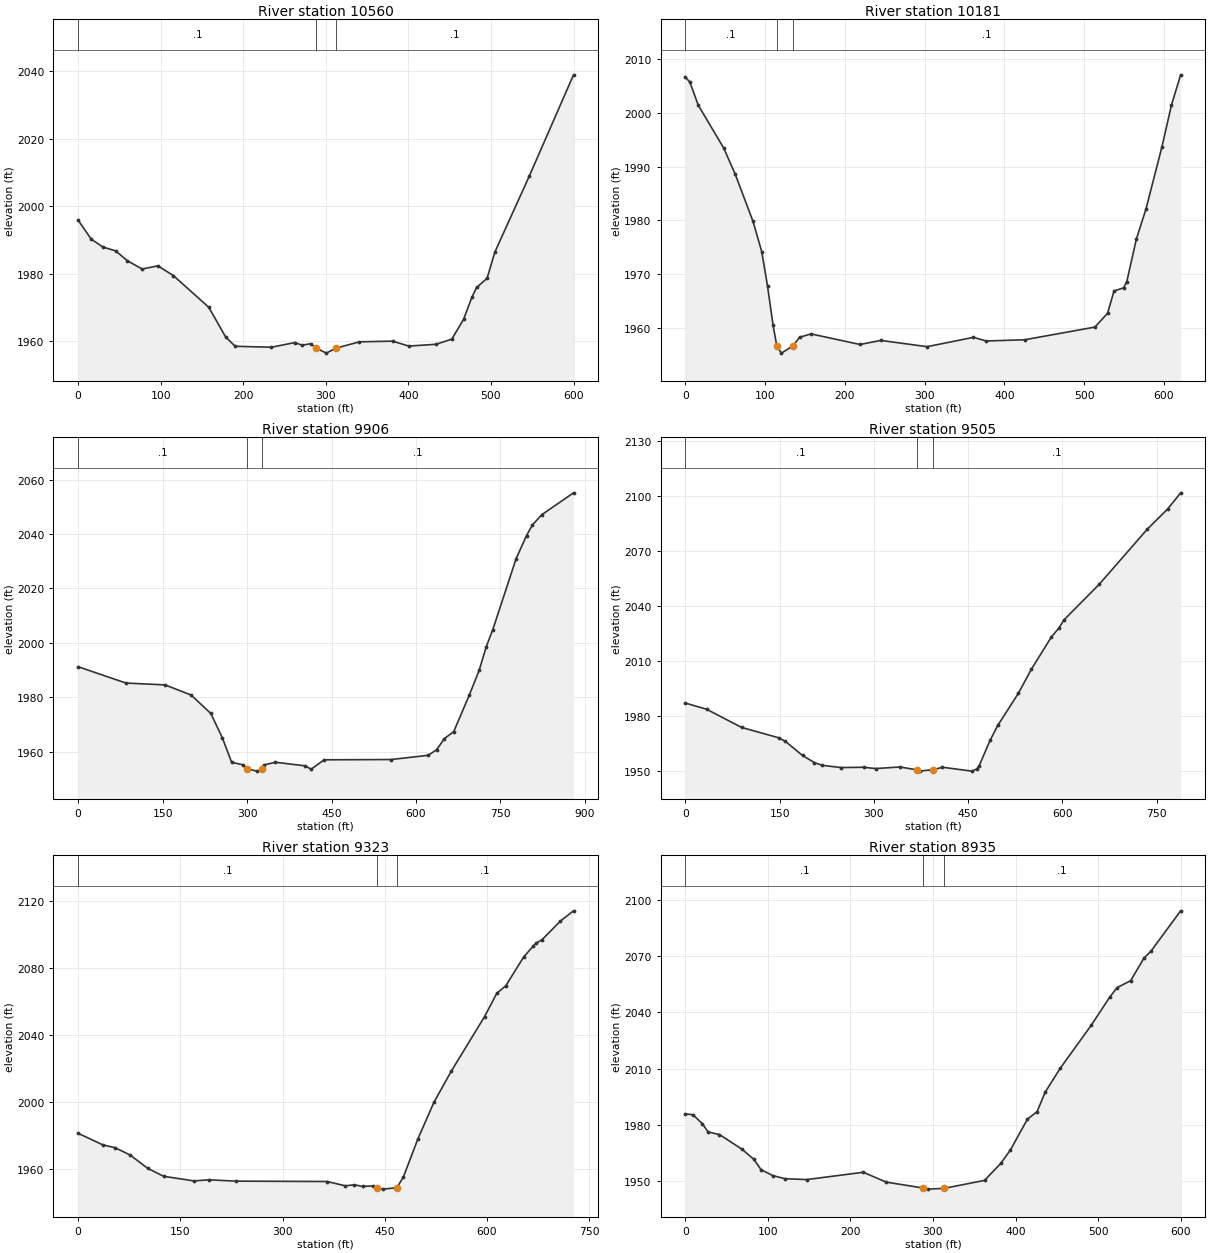
Type RM Length L Ch R = 1 ,10560   ,379.1,379.1,379.1
XS GIS Cut Line= 2
2293889.44340747728234.4184330392293383.92066563727911.236197311
#Sta/Elev= 30
       0 1995.82    15.7 1990.23      30 1987.86    45.3 1986.74    59.7 1983.79
    77.5 1981.35    96.5  1982.3   115.4 1979.39   158.2 1970.01   178.5 1961.26
   190.1 1958.46   234.1 1958.18   262.5 1959.56   271.2 1958.78   281.6 1959.23
  288.461957.893   300.6 1956.43  312.121957.892   340.7 1959.78     381 1959.98
   400.3 1958.52   433.5 1959.05   452.5 1960.57   466.8 1966.43   476.8 1972.92
   482.6  1975.9   495.3 1978.59   504.7 1986.37   546.3 2008.83     600  2038.9
#Mann= 3 ,-1,0
       0      .1       0  288.46    .045       0  312.12      .1       0
Bank Sta=288.46,312.12
XS Rating Curve= 0 ,0
Exp/Cntr(USF)=0,0
Exp/Cntr=0.3,0.1

Type RM Length L Ch R = 1 ,10181   ,275.1,275.1,275.1
XS GIS Cut Line= 3
 2293988.8998889 728010.863307572293685.90571657727817.375976657
2293424.64483237727811.115161042
#Sta/Elev= 30
       0 2006.66     5.6 2005.79    16.2 2001.46    48.3 1993.41    62.6 1988.58
    84.9 1979.79    95.8 1974.16   103.1 1967.71     110 1960.46   114.8 1956.52
   120.5 1955.27     135 1956.62   143.2 1958.22   157.5 1958.85     219 1956.88
     245 1957.64     303 1956.47   361.1 1958.21     377 1957.53   425.3 1957.76
   513.3 1960.12   529.2 1962.69   537.3 1966.85   549.3 1967.43   553.3 1968.59
   565.3  1976.5   577.3 1982.09   597.3 1993.66   609.3 2001.47   620.8  2007.1
#Mann= 3 ,-1,0
       0      .1       0   114.8    .045       0     135      .1       0
Bank Sta=114.8,135
XS Rating Curve= 0 ,0
Exp/Cntr(USF)=0,0
Exp/Cntr=0.3,0.1

Type RM Length L Ch R = 1 ,9906    ,401,401,401
XS GIS Cut Line= 3
 2294113.6731916 727765.927888212293923.30827814 727655.60264128
2293281.01436177727806.353153498
#Sta/Elev= 30
       0 1991.24    84.9 1985.25   154.3 1984.57   200.7 1980.84   235.6 1974.07
   256.1 1965.12   272.5 1956.16   293.1  1955.2300.21991953.724   317.7  1952.9
325.89981953.682   330.1 1955.19   350.4 1956.15   403.6 1954.84   413.6 1953.59
   436.9 1957.06     556 1957.16   621.8 1958.72   636.6 1960.76   650.5 1964.85
     667 1967.39   694.6 1980.79   712.2 1989.92   724.5 1998.43   736.4 2004.88
   777.9 2030.98   796.3 2039.42   806.7 2043.29   823.1 2047.04   879.8 2055.12
#Mann= 3 ,-1,0
       0      .1       0300.2199    .045       0325.8998      .1       0
Bank Sta=300.2199,325.8998
XS Rating Curve= 0 ,0
Exp/Cntr(USF)=0,0
Exp/Cntr=0.3,0.1

Type RM Length L Ch R = 1 ,9505    ,181.3,181.3,181.3
XS GIS Cut Line= 3
2294021.99851072727618.4710700752293768.40683038727184.058602948
2293741.53101296 726900.36516733
#Sta/Elev= 30
       0 1987.08    33.9 1983.69    89.5 1973.76   148.5 1968.11     159 1966.19
   186.5 1958.43   205.3 1954.55   217.8 1953.05   247.9 1951.84     284 1951.99
   302.6 1951.28   341.5 1952.15367.99951950.595   373.7 1949.95394.79951950.684
   409.1    1952   455.9 1949.88   463.8 1951.03   467.3 1952.66   484.8 1966.68
   497.1 1974.85     530  1992.5   550.3 2005.41   582.2 2023.07   594.3 2028.07
   602.3 2032.45   658.6 2052.01   734.9 2082.06   767.1 2092.99     788 2101.93
#Mann= 3 ,-1,0
       0      .1       0367.9995    .045       0394.7995      .1       0
Bank Sta=367.9995,394.7995
XS Rating Curve= 0 ,0
Exp/Cntr(USF)=0,0
Exp/Cntr=0.3,0.1

Type RM Length L Ch R = 1 ,9323    ,388.4,388.4,388.4
XS GIS Cut Line= 2
2294140.72388539727562.0575896022293824.16877578726907.753210842
#Sta/Elev= 30
       0  1981.5    36.5 1974.59    54.3 1972.96    76.5 1968.53   102.3 1960.59
   125.4 1955.93   169.8 1953.18     192 1953.83   231.7 1953.05   365.3 1952.82
     392 1950.27   405.4 1950.87   417.3  1949.9     432 1950.18   438.21949.142
   447.3 1948.29  467.681949.142   477.2 1955.52   498.7 1978.38   522.1 2000.05
   547.5 2018.53   596.4 2051.07   614.2 2064.86   627.5 2069.39   653.9 2086.65
   667.5 2092.88   671.7 2094.65   680.9 2096.89   707.5 2107.86   726.9 2114.01
#Mann= 3 ,-1,0
       0      .1       0   438.2    .045       0  467.68      .1       0
Bank Sta=438.2,467.68
XS Rating Curve= 0 ,0
Exp/Cntr(USF)=0,0
Exp/Cntr=0.3,0.1

Type RM Length L Ch R = 1 ,8935    ,428.5,428.5,428.5
XS GIS Cut Line= 2
2294472.31623717727377.251372281 2294178.5462736726854.088674351
#Sta/Elev= 30
       0 1985.87     9.3 1985.38    20.7 1980.59    27.6  1976.2    41.4 1974.83
    68.9 1966.95    82.7 1961.76    91.8 1956.13   105.9 1952.98   120.6 1951.31
     147 1950.84   215.7 1954.73   243.2  1949.5  288.211946.347   293.7 1945.75
  313.141946.138   362.5 1950.41   382.1 1959.46   393.8 1966.61   414.4 1983.03
   426.1 1987.02   435.9 1997.41   454.2 2010.18   491.6    2033   513.9 2047.91
   523.1 2053.14   539.5 2056.83   555.4 2068.75   564.2 2072.63     600 2094.04
#Mann= 3 ,-1,0
       0      .1       0  288.21    .045       0  313.14      .1       0
Bank Sta=288.21,313.14
XS Rating Curve= 0 ,0
Exp/Cntr(USF)=0,0
Exp/Cntr=0.3,0.1

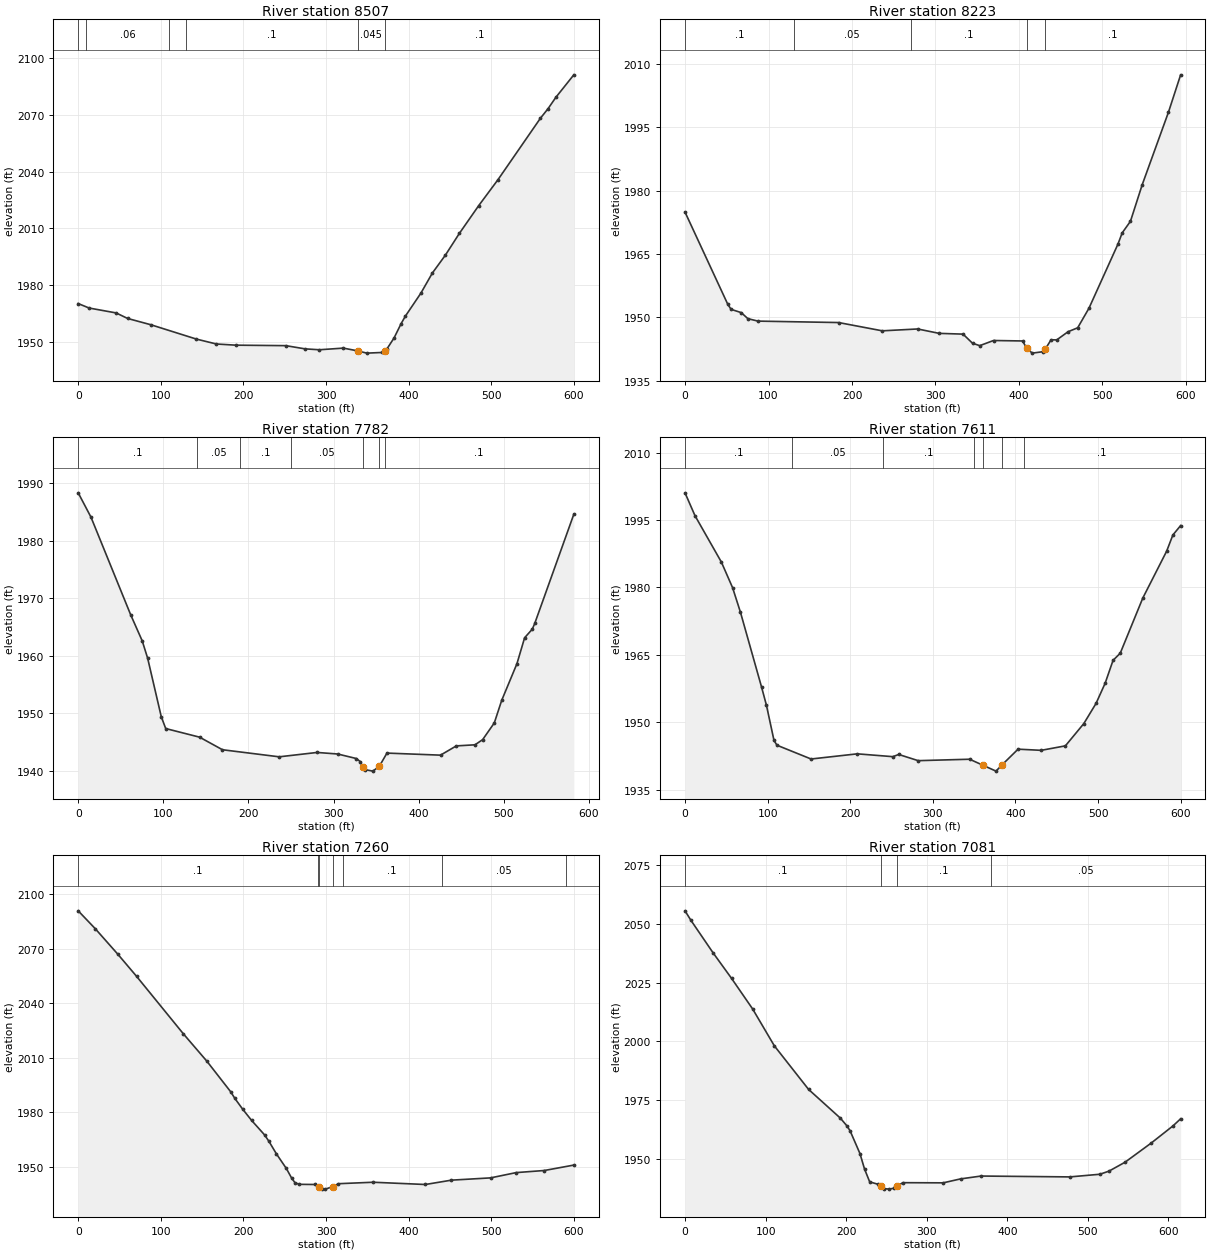
Type RM Length L Ch R = 1 ,8507    ,283.5,283.5,283.5
XS GIS Cut Line= 2
2294785.45467947727184.4986844152294475.90725659 726670.51386656
#Sta/Elev= 30
       0 1970.24    13.2 1967.88    45.9 1965.29    59.9 1962.35    87.9 1959.05
   143.2 1951.44   167.3 1948.86   190.7 1948.24   251.4 1947.98   274.7 1946.28
   291.9 1945.81     321 1946.68  338.321945.226   349.4 1944.03   368.1 1944.38
  371.411945.227   373.5 1946.09   382.4 1952.06   390.9  1959.6   396.1  1963.6
   414.8  1975.7   428.8 1986.41   444.4 1995.76   461.5 2007.38   484.8 2021.99
   508.2 2035.75   559.5 2068.19   568.9 2073.35   578.2 2079.25     600 2091.19
#Mann= 6 ,-1,0
       0      .1       0      10     .06       0     110     .07       0
     130      .1       0  338.32    .045       0  371.41      .1       0
Bank Sta=338.32,371.41
XS Rating Curve= 0 ,0
Exp/Cntr(USF)=0,0
Exp/Cntr=0.3,0.1

Type RM Length L Ch R = 1 ,8223    ,441.3,441.3,441.3
XS GIS Cut Line= 3
2294971.78921017727108.0672199332294945.82787143726869.367978229
2294736.11214778726584.825963379
#Sta/Elev= 30
       0 1974.96    51.2 1953.13    55.2 1951.92    67.3 1951.16    75.3 1949.72
    87.4 1949.14     184  1948.8   236.3 1946.84   278.6 1947.28   304.4 1946.24
     333 1946.06   344.4 1943.89     353 1943.33   369.5 1944.55   404.3 1944.44
   409.3  1942.7   415.9 1941.56   429.2 1941.91   431.7 1942.58   438.4 1944.72
   445.2 1944.69   458.8 1946.63   470.3 1947.56   483.8 1952.19   518.6 1967.41
   523.6 1970.03   533.5 1972.78   547.5 1981.39     579  1998.6   593.6 2007.46
#Mann= 5 ,-1,0
       0      .1       0     130     .05       0  270.11      .1       0
   409.3    .045       0   431.7      .1       0
Bank Sta=409.3,431.7
XS Rating Curve= 0 ,0
Exp/Cntr(USF)=0,0
Exp/Cntr=0.3,0.1

Type RM Length L Ch R = 1 ,7782    ,170.2,170.2,170.2
XS GIS Cut Line= 2
2295310.98816324726900.1153109792295045.86777177726381.818475165
#Sta/Elev= 30
       0 1988.35      15 1984.12    61.7 1967.11    75.2 1962.59    81.6 1959.56
    97.6 1949.38   102.8 1947.33   142.6 1945.83   169.5 1943.64   236.1 1942.41
   280.7 1943.17   304.8  1942.9   326.8 1942.11   331.3 1941.58   334.2 1940.68
   337.2 1940.17   346.1 1939.92   353.7 1940.75   362.7 1943.06   425.6  1942.7
   444.2 1944.31   466.1  1944.5   475.1  1945.4   488.8 1948.31   497.5 1952.24
   515.4 1958.62   524.4 1963.13   533.4 1964.62   536.3 1965.62   582.2 1984.62
#Mann= 7 ,-1,0
       0      .1       0     140     .05       0     190      .1       0
     250     .05       0   334.2    .045       0   353.7     .05       0
     360      .1       0
Bank Sta=334.2,353.7
XS Rating Curve= 0 ,0
Exp/Cntr(USF)=0,0
Exp/Cntr=0.3,0.1

Type RM Length L Ch R = 1 ,7611    ,351.5,351.5,351.5
XS GIS Cut Line= 2
2295420.59640588726795.7777799512295133.41766183726268.968166368
#Sta/Elev= 30
       0 2001.07    12.1 1995.97      44 1985.66    57.6 1979.94    67.1 1974.49
    92.8 1957.73    98.6 1953.75   107.7 1945.95   111.3 1944.87   152.6  1941.8
   208.6 1942.95   251.6 1942.32   258.7 1942.81   282.3 1941.43   344.6 1941.75
   360.41940.431   376.5  1939.1  383.441940.432   403.2 1943.99   431.2 1943.73
   460.5 1944.73   482.8 1949.69   497.6 1954.18   508.6 1958.67   518.2 1963.77
   526.9 1965.36   554.2 1977.64   583.1 1988.09   590.6 1991.68     600 1993.78
#Mann= 7 ,-1,0
       0      .1       0     130     .05       0     240      .1       0
     350     .05       0   360.4    .045       0  383.44     .05       0
     410      .1       0
Bank Sta=360.4,383.44
XS Rating Curve= 0 ,0
Exp/Cntr(USF)=0,0
Exp/Cntr=0.3,0.1

Type RM Length L Ch R = 1 ,7260    ,179,179,179
XS GIS Cut Line= 2
2295704.01649543726728.8139879792295314.44601891726272.486426004
#Sta/Elev= 30
       0 2090.84    20.6 2081.03    47.9 2066.99    70.6 2054.81   127.3 2023.13
   155.7 2008.09   184.6 1991.22   189.7 1987.52   199.4 1981.46   209.9 1975.46
   225.7 1967.43   230.9 1963.93     240    1957     252 1948.97   258.5  1943.6
   262.5 1941.12   267.7 1940.25   286.2 1940.16  291.181939.042   294.7 1937.86
   299.3 1937.61   308.41939.042   315.1  1940.6   357.1  1941.4   420.3 1940.16
   451.8 1942.55   499.2  1943.8   530.2 1946.71   564.2 1947.86     600 1950.85
#Mann= 7 ,-1,0
       0      .1       0     290     .05       0  291.18    .045       0
   308.4     .05       0     320      .1       0     440     .05       0
     590      .1       0
Bank Sta=291.18,308.4
XS Rating Curve= 0 ,0
Exp/Cntr(USF)=0,0
Exp/Cntr=0.3,0.1

Type RM Length L Ch R = 1 ,7081    ,463.4,463.4,463.4
XS GIS Cut Line= 2
2295779.08324988726572.6781555162295374.13936127726109.655872097
#Sta/Elev= 30
       0 2055.66     7.4 2051.58    34.8 2037.77    57.8 2026.84    83.9 2013.83
   110.9 1998.08   153.4  1979.5   192.8 1967.27   201.3 1963.82   204.9 1961.84
   217.1 1952.18   222.8 1945.57   229.2 1940.09   239.8 1939.05  243.41 1938.24
   247.5 1937.21   253.5    1937   259.6 1937.43  263.171938.239   270.3 1939.75
   320.4 1939.68   341.9 1941.36   367.4 1942.58   477.6 1942.21   514.8 1943.34
   526.1 1944.66     546 1948.45   578.6 1956.65   605.5 1963.93   615.1 1966.99
#Mann= 4 ,-1,0
       0      .1       0  243.41    .045       0  263.17      .1       0
     380     .05       0
Bank Sta=243.41,263.17
XS Rating Curve= 0 ,0
Exp/Cntr(USF)=0,0
Exp/Cntr=0.3,0.1

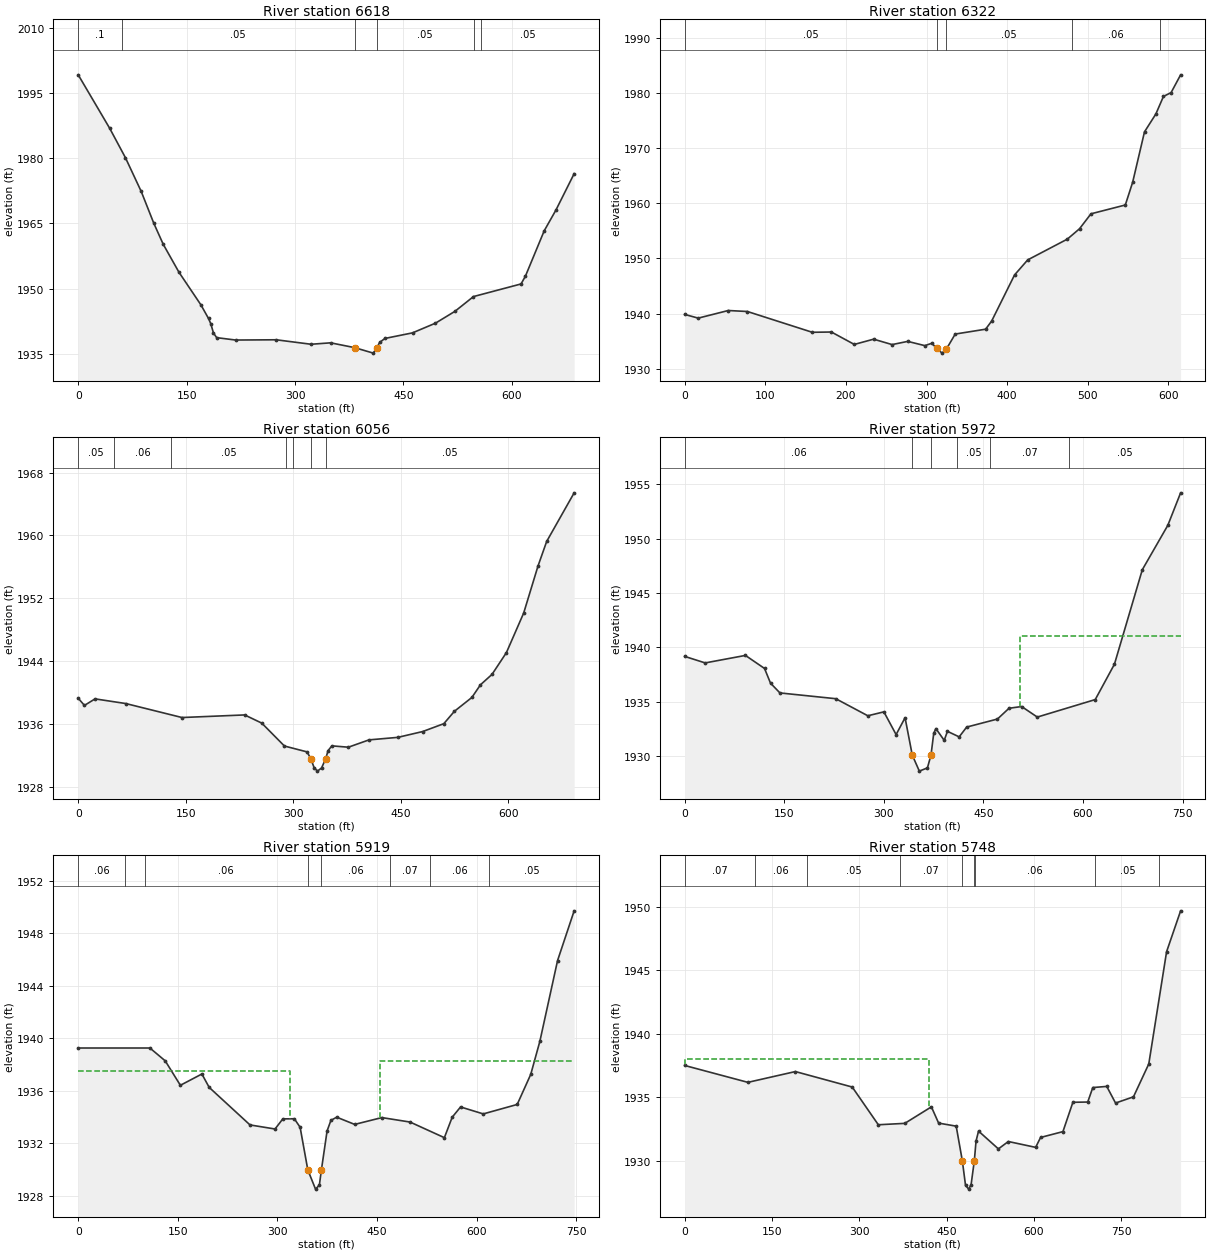
Type RM Length L Ch R = 1 ,6618    ,295.5,295.5,295.5
XS GIS Cut Line= 3
2295928.83559182726341.2927346552295847.20484437726150.728043799
2295527.12021913725794.450679555
#Sta/Elev= 30
       0 1999.17    43.6 1986.86    65.4 1980.09    87.2 1972.34   104.6 1965.03
   117.6 1960.21   139.4 1953.77   169.8 1946.26   180.3 1943.13   183.4 1941.95
   187.2 1939.78   191.6 1938.72   217.8 1938.17   273.9 1938.23   322.3  1937.2
   349.3 1937.53  382.34 1936.43   408.4 1935.16  413.111936.432   417.3 1937.65
   424.5 1938.54   462.6 1939.82   494.4 1942.05   521.3 1944.77     547 1948.17
   612.8 1951.07   618.8 1952.84   644.9 1963.31   661.1 1968.07   686.3 1976.44
#Mann= 6 ,-1,0
       0      .1       0      60     .05       0  382.34    .045       0
  413.11     .05       0  547.31     .06       0  557.31     .05       0
Bank Sta=382.34,413.11
XS Rating Curve= 0 ,0
Exp/Cntr(USF)=0,0
Exp/Cntr=0.3,0.1

Type RM Length L Ch R = 1 ,6322    ,265.5,265.5,265.5
XS GIS Cut Line= 2
2296109.85958886725954.6224762462295590.18573213725625.309309828
#Sta/Elev= 30
       0 1939.84    16.8 1939.17    54.1 1940.55    77.8 1940.37   158.3  1936.6
     182 1936.65   210.4  1934.4   234.4 1935.35   257.3 1934.37   276.7 1934.95
   297.9 1934.18   306.6 1934.61   312.4  1933.7   319.3 1932.82  324.471933.512
   335.6 1936.28   373.3 1937.16   380.8 1938.64   409.2    1947   425.5 1949.73
   474.7  1953.5   489.8 1955.38     504 1958.09   546.6 1959.69   555.7 1963.81
   570.4 1972.96   584.5  1976.2   593.9 1979.38   603.4 1980.08   615.2  1983.3
#Mann= 5 ,-1,0
       0     .05       0   312.4    .045       0  324.47     .05       0
     480     .06       0     590     .05       0
Bank Sta=312.4,324.47
XS Rating Curve= 0 ,0
Exp/Cntr(USF)=0,0
Exp/Cntr=0.3,0.1

Type RM Length L Ch R = 1 ,6056    ,84.8,84.8,84.8
XS GIS Cut Line= 3
2296180.91807533725840.5305588712295909.14970041725445.010513221
2295698.04390917725425.598486441
#Sta/Elev= 30
       0 1939.32     8.7 1938.41    23.5 1939.24    66.2 1938.65   144.8 1936.87
   232.2  1937.2   256.1 1936.16   287.7 1933.25   319.4  1932.5   324.4 1931.64
   329.2 1930.49   333.8 1930.06   339.5 1930.46   345.3 1931.64   348.6 1932.67
   353.9 1933.27   376.9  1933.1   405.7 1934.03   445.9 1934.35   480.6 1935.09
   510.1 1936.09   524.8 1937.66   549.2 1939.42   561.2 1941.03   577.3 1942.35
   597.4 1945.12   621.5 1950.15   641.5 1956.13   653.6 1959.25   691.9 1965.42
#Mann= 7 ,-1,0
       0     .05       0      50     .06       0     130     .05       0
     290     .06       0     300     .05       0   324.4    .045       0
   345.3     .05       0
Bank Sta=324.4,345.3
XS Rating Curve= 0 ,0
Exp/Cntr(USF)=0,0
Exp/Cntr=0.3,0.1

Type RM Length L Ch R = 1 ,5972    ,52.5,52.5,52.5
XS GIS Cut Line= 3
2296228.65017219725794.5938339492295930.75300043725321.886148447
2295754.11872087725387.247727613
#Sta/Elev= 30
       0 1939.17    30.9 1938.57    91.5 1939.26   120.3 1938.06   129.3 1936.71
   143.5 1935.81   227.6 1935.28   275.9 1933.71   300.1 1934.07   318.5 1931.98
     332 1933.53  342.841930.098   353.5 1928.62   365.7 1928.92  371.071930.101
   375.2  1932.1   378.4 1932.53     391 1931.45   395.8 1932.28   413.5 1931.77
   424.8 1932.67   471.2 1933.41   488.6  1934.4   507.6 1934.56   531.2 1933.59
   618.5  1935.2   647.4 1938.45   689.4 1947.14   727.8 1951.22   747.1 1954.21
#Mann= 6 ,-1,0
       0     .06       0  342.84    .045       0  371.07     .06       0
     410     .05       0     460     .07       0  578.74     .05       0
#XS Ineff= 2 , 0
                          505.14         1941.02
Permanent Ineff=
       F       F
Bank Sta=342.84,371.07
XS Rating Curve= 0 ,0
Exp/Cntr(USF)=0,0
Exp/Cntr=0.3,0.1

Type RM Length L Ch R = 1 ,5919    ,171.4,171.4,171.4
XS GIS Cut Line= 3
2296262.24794288725756.1053100942295964.35077112725283.397624592
2295787.71649157725348.759203758
#Sta/Elev= 30
       0 1939.27     108 1939.27   131.1 1938.29   153.9 1936.43   186.3 1937.29
   197.3 1936.27   258.8 1933.41   296.5  1933.1   308.2 1933.87   325.6 1933.88
   334.3 1933.23  345.881929.984   357.5 1928.52   363.3 1928.83  366.351929.984
   374.9 1932.95   380.7 1933.76   389.4    1934   416.5 1933.45   457.4 1933.97
   499.9 1933.63   551.6 1932.44   563.4    1934     576 1934.78   610.2 1934.25
   661.3 1934.97   681.7 1937.26   695.4 1939.77   722.1 1945.93   747.1 1949.72
#Mann= 8 ,-1,0
       0     .06       0      70     .05       0     100     .06       0
  345.88    .045       0  366.35     .06       0     470     .07       0
     530     .06       0  618.74     .05       0
#XS Ineff= 2 , 0
          319.28 1937.55  454.04         1938.29
Permanent Ineff=
       F       F
Bank Sta=345.88,366.35
XS Rating Curve= 0 ,0
Exp/Cntr(USF)=0,0
Exp/Cntr=0.3,0.1

Type RM Length L Ch R = 1 ,5748    ,145.8,145.8,145.8
XS GIS Cut Line= 4
2296355.62631636725692.5138546712296190.62408872725318.832339149
2295921.28221715  725219.34570192295778.11851964725282.434788936
#Sta/Elev= 30
       0 1937.49   108.6 1936.16   190.2 1937.01   287.9 1935.79   332.7 1932.82
   378.2 1932.93   423.9 1934.23   436.3 1932.95   466.5 1932.71   477.1 1929.97
   482.5 1928.06   487.9 1927.75   492.1  1928.1   497.7    1930   500.6 1931.53
   504.9 1932.32     539 1930.92   556.1  1931.5     603 1931.04   611.5 1931.82
   649.9 1932.28     667 1934.59   692.5 1934.61   701.2 1935.75   725.2 1935.84
   740.3 1934.53   771.1 1935.02   797.4 1937.61     828 1946.45   852.1 1949.67
#Mann= 9 ,-1,0
       0     .07       0     120     .06       0     210     .05       0
     370     .07       0   477.1    .045       0   497.7     .07       0
  498.49     .06       0  705.62     .05       0  815.62      .1       0
#XS Ineff= 2 , 0
        419.4377    1938
Permanent Ineff=
       F       F
Bank Sta=477.1,497.7
XS Rating Curve= 0 ,0
Exp/Cntr(USF)=0,0
Exp/Cntr=0.3,0.1