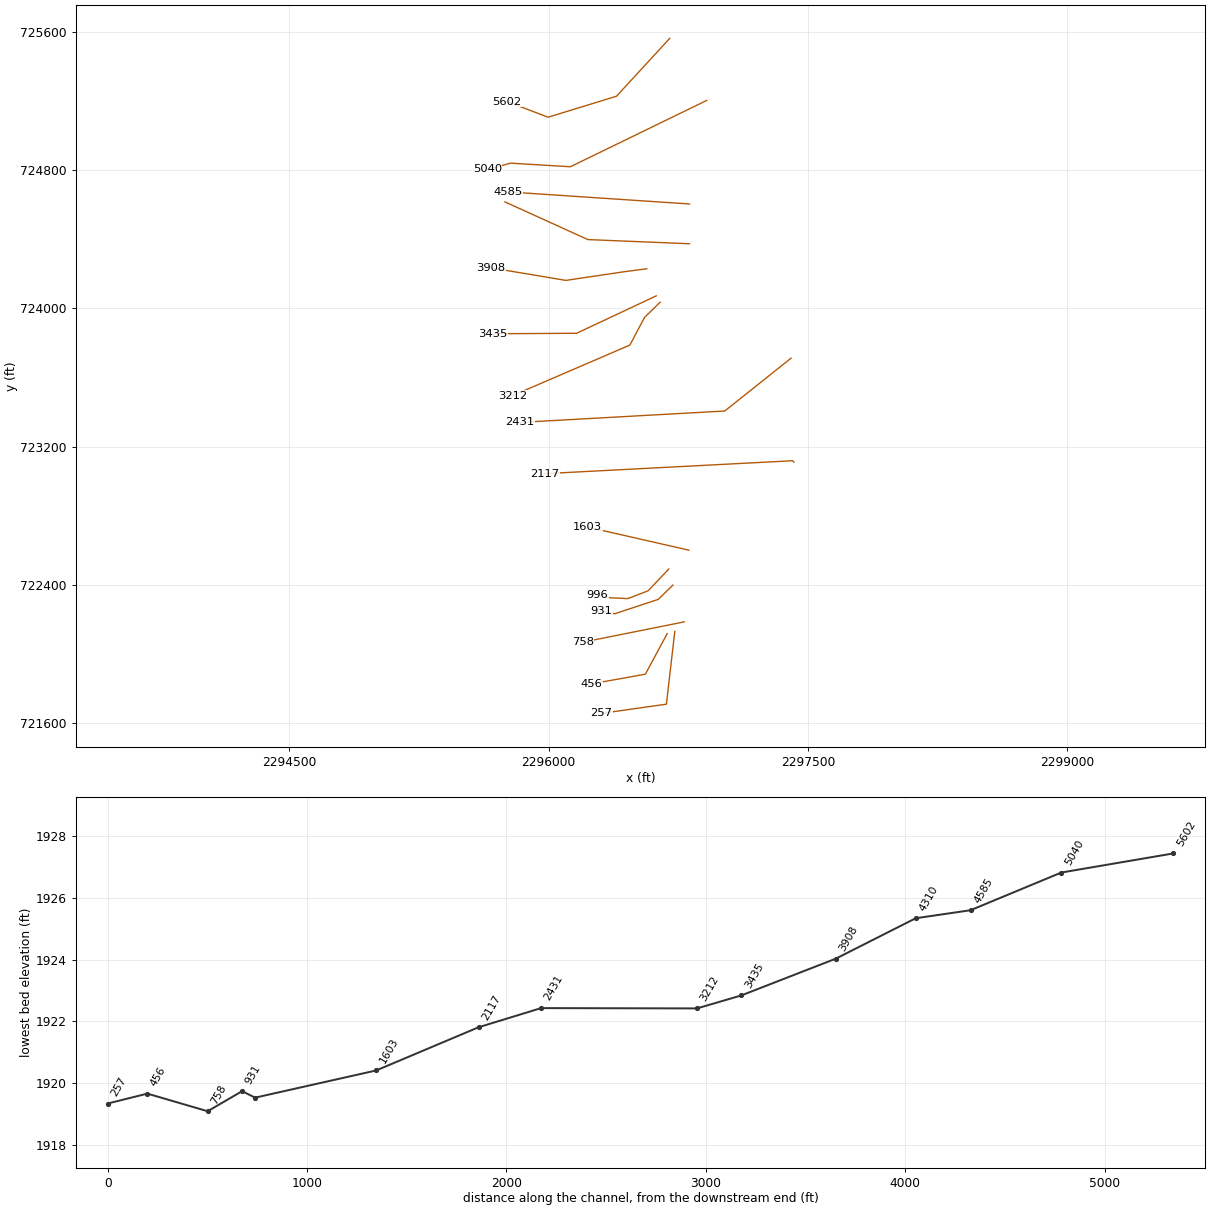
HEC-RAS study PEARCYRN.prj: PEARCYRN

--- PEARCYRN.g01 (geometry) --- (continued)

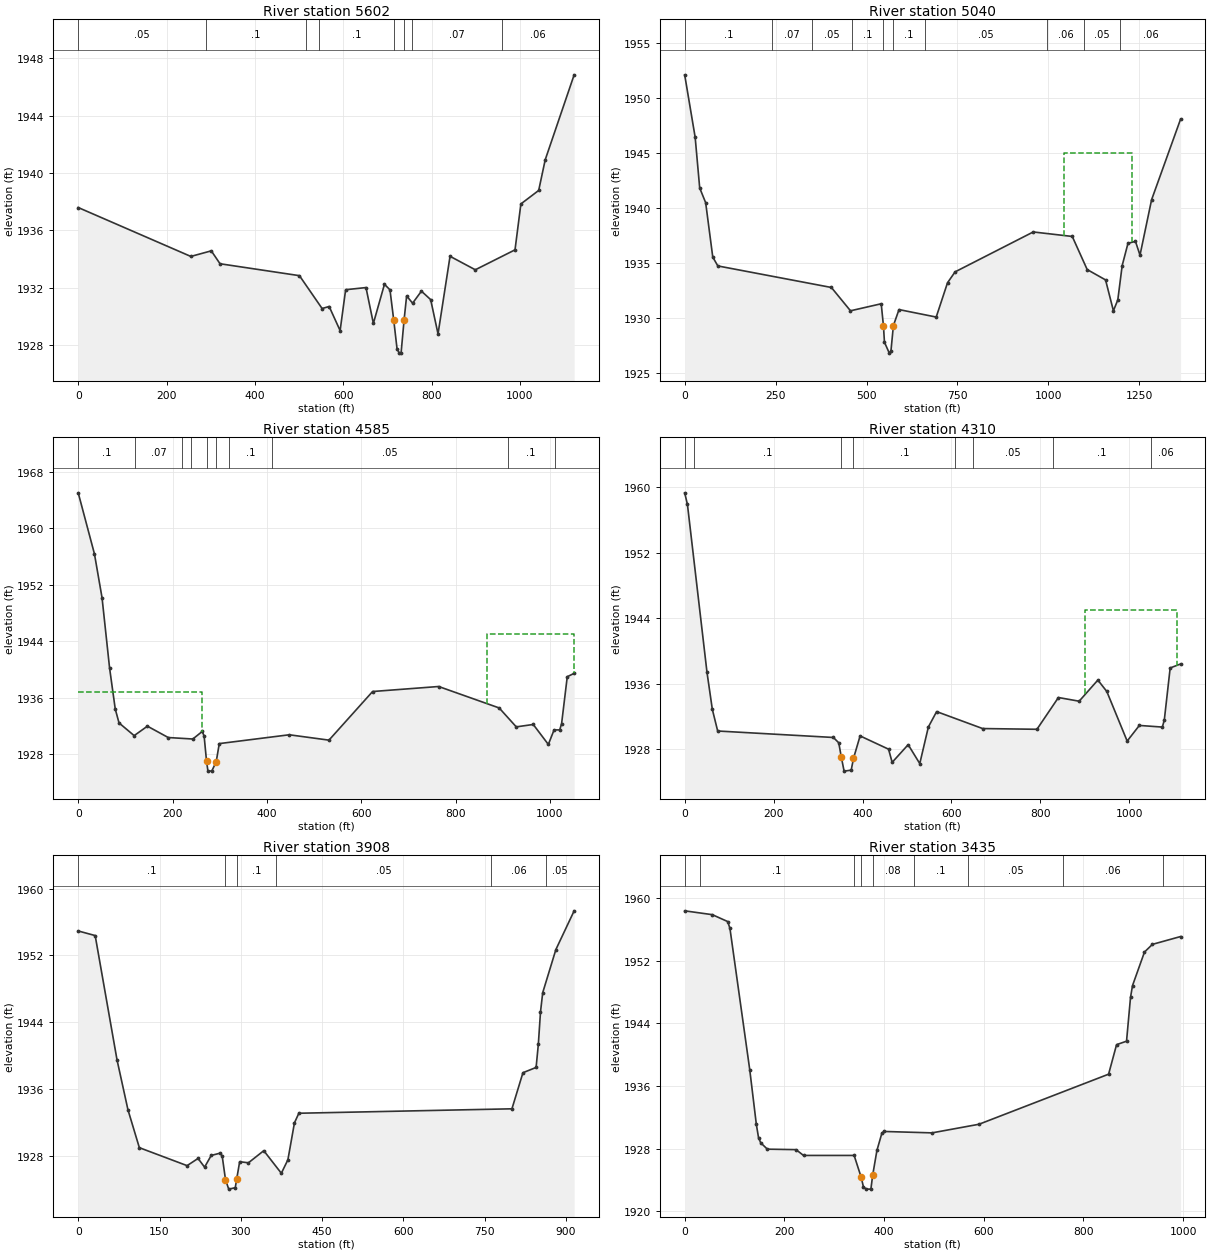
Type RM Length L Ch R = 1 ,5602    ,562.5,562.5,562.5
XS GIS Cut Line= 4
2296700.18979171725561.4826739032296392.02386657725226.625211942
2295996.50382092725105.3000445652295759.01785502725195.607794255
#Sta/Elev= 30
       0 1937.59     255 1934.18   301.3 1934.57   321.1 1933.67   500.9 1932.84
   552.2 1930.55   568.2 1930.69     593 1929.01   605.5 1931.86   651.6 1932.01
   668.3 1929.51   693.4 1932.24   705.9 1931.85   714.3 1929.77   721.9 1927.74
   726.9 1927.44   731.1 1927.47   737.9 1929.77   743.6 1931.43   757.1 1930.92
   777.1 1931.76     798 1931.17   814.7 1928.78   841.9 1934.19   899.1 1933.25
     989 1934.64  1002.3 1937.84  1042.6 1938.78  1057.4 1940.92  1122.9 1946.84
#Mann= 8 ,-1,0
       0     .05       0     290      .1       0  515.08     .07       0
  545.08      .1       0   714.3    .045       0   737.9      .1       0
  755.08     .07       0  958.79     .06       0
Bank Sta=714.3,737.9
XS Rating Curve= 0 ,0
Exp/Cntr(USF)=0,0
Exp/Cntr=0.3,0.1

Type RM Length L Ch R = 1 ,5040    ,455.1,455.1,455.1
XS GIS Cut Line= 4
2296914.09732518725202.4387986182296125.46889717724818.787090451
2295779.29977709724839.627386386  2295644.296917 724803.22028241
#Sta/Elev= 30
       0 1952.13    28.8 1946.46    41.3 1941.84    57.7  1940.5    77.2 1935.56
    91.1 1934.75   403.4 1932.79   455.9 1930.67   540.4 1931.31546.56791929.281
   549.3 1927.81   562.6 1926.82   567.1    1927   573.9 1929.33   589.3 1930.78
   691.6  1930.1   722.7 1933.22   743.5 1934.21   958.4 1937.84  1065.7 1937.43
  1106.7 1934.42  1157.2 1933.48  1178.8 1930.67  1190.9 1931.66  1202.9 1934.78
  1218.9 1936.81  1239.5 1936.98  1251.9 1935.73  1283.8 1940.77  1363.6 1948.11
#Mann= 10 ,-1,0
       0      .1       0     240     .07       0     350     .05       0
     460      .1       0546.5679    .045       0   573.9      .1       0
     660     .05       0     997     .06       0    1097     .05       0
    1197     .06       0
#XS Ineff= 1 ,-1
1043.5051228.907    1945
Permanent Ineff=
       F
Bank Sta=546.5679,573.9
XS Rating Curve= 0 ,0
Exp/Cntr(USF)=0,0
Exp/Cntr=0.3,0.1

Type RM Length L Ch R = 1 ,4585    ,275,275,275
XS GIS Cut Line= 2
2296814.51414529724603.3369750942295765.65809942724673.277889574
#Sta/Elev= 30
       0 1965.03    34.4 1956.38    50.5 1950.17    66.5  1940.2    78.5  1934.4
    86.5 1932.43   118.6 1930.63   146.7 1931.97   190.8 1930.36   242.9 1930.15
   262.9 1931.22   266.9 1930.57272.03921926.983   274.9 1925.65     283  1925.6
292.48921926.922     299  1929.5   447.3 1930.75   531.5 1929.99     624 1936.88
     764 1937.59   892.3 1934.55   928.5 1931.87   964.5 1932.21   996.5 1929.38
  1008.6 1931.44  1020.6 1931.44  1024.6 1932.33  1036.6 1938.98  1051.2 1939.45
#Mann= 10 ,-1,0
       0      .1       0     120     .07       0     220      .1       0
     240     .07       0272.0392    .045       0292.4892     .07       0
     320      .1       0     410     .05       0     910      .1       0
    1010     .06       0
#XS Ineff= 2 , 0
           263.2 1936.81866.7678            1945
Permanent Ineff=
       F       F
Bank Sta=272.0392,292.4892
XS Rating Curve= 0 ,0
Exp/Cntr(USF)=0,0
Exp/Cntr=0.3,0.1

Type RM Length L Ch R = 1 ,4310    ,401.2,401.2,401.2
XS GIS Cut Line= 3
2296814.33759143724373.403624774 2296226.7559024724397.493128949
2295746.71231775724615.582683539
#Sta/Elev= 30
       0 1959.33     6.2 1957.91    50.2  1937.4    62.2 1932.88    74.2 1930.24
   334.4 1929.45   346.5  1928.8352.23791927.054   358.5 1925.34   374.5 1925.46
379.58781926.885   394.5 1929.64   458.5 1928.02   466.6 1926.41   502.6 1928.57
   528.7 1926.26     548 1930.73   566.6 1932.61     670 1930.54   792.2 1930.45
   840.5 1934.33   887.1 1933.88   929.2 1936.46   949.3 1935.07   995.1 1929.01
  1022.5 1930.92  1074.2 1930.72  1078.6 1931.57  1091.8 1937.94  1115.3 1938.43
#Mann= 8 ,-1,0
       0     .05       0      20      .1       0352.2379    .045       0
379.5878      .1       0  608.08     .08       0  648.08     .05       0
  828.08      .1       0 1048.08     .06       0
#XS Ineff= 1 ,-1
900.81741106.116    1945
Permanent Ineff=
       F
Bank Sta=352.2379,379.5878
XS Rating Curve= 0 ,0
Exp/Cntr(USF)=0,0
Exp/Cntr=0.3,0.1

Type RM Length L Ch R = 1 ,3908    ,473.6,473.6,473.6
XS GIS Cut Line= 4
2296567.20314996724228.6204506862296432.93447813724211.061833573
2296099.51914814724161.5000953332295662.97139116724234.434733472
#Sta/Elev= 30
       0 1954.92    31.3 1954.37    71.6  1939.5    91.8 1933.52   112.8 1928.99
   200.9 1926.84   221.1  1927.7   233.2 1926.66   245.4 1928.06   261.5 1928.33
   265.6 1928.02  271.741925.182   277.7 1924.03   289.8  1924.2   292.31925.185
   297.9 1927.31   314.1 1927.18   342.4 1928.63   374.8 1925.93   386.9 1927.54
     399 1931.96   407.1 1933.11   800.3 1933.64   820.6 1937.96   844.9 1938.59
     849 1941.35     853 1945.23   857.1 1947.54   881.4  1952.7   915.1 1957.33
#Mann= 6 ,-1,0
       0      .1       0  271.74    .045       0   292.3      .1       0
  365.41     .05       0  762.49     .06       0  862.49     .05       0
Bank Sta=271.74,292.3
XS Rating Curve= 0 ,0
Exp/Cntr(USF)=0,0
Exp/Cntr=0.3,0.1

Type RM Length L Ch R = 1 ,3435    ,222.2,222.2,222.2
XS GIS Cut Line= 3
2296622.32502037724072.1674919822296161.50604855723855.650820581
2295675.63863994 723852.78676388
#Sta/Elev= 30
       0 1958.36    55.4 1957.87    86.3 1956.99    90.8 1956.12   130.5  1938.1
   143.8 1931.09   148.2  1929.4   152.6 1928.75   165.9 1927.94   223.4 1927.88
   238.4 1927.14     340 1927.14354.12811924.348   358.7 1923.11   364.5 1922.84
   373.6 1922.84377.11791924.596   385.7 1927.78   395.7 1929.99   400.1  1930.2
   496.2 1930.02   590.5 1931.12   850.5 1937.51   866.5 1941.28   886.5 1941.72
   894.5 1947.32   898.5 1948.82   922.5  1953.1   938.4 1954.08     995 1955.08
#Mann= 9 ,-1,0
       0     .05       0      30      .1       0     340     .08       0
354.1281    .045       0377.1179     .08       0     460      .1       0
  569.15     .05       0  759.15     .06       0  959.15      .1       0
Bank Sta=354.1281,377.1179
XS Rating Curve= 0 ,0
Exp/Cntr(USF)=0,0
Exp/Cntr=0.3,0.1

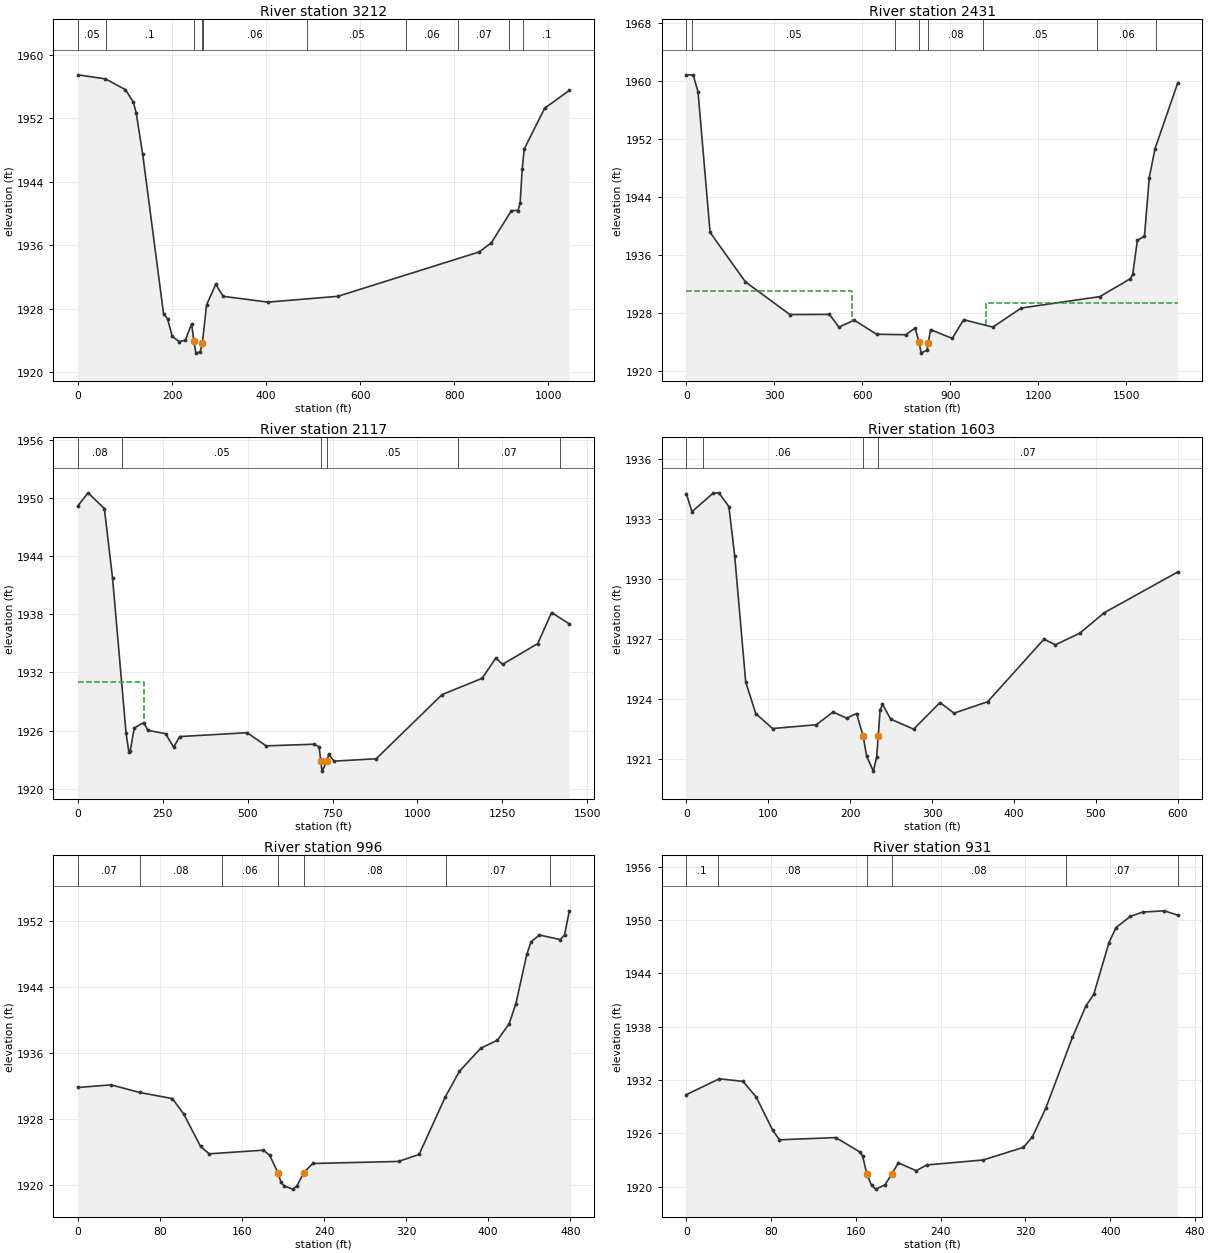
Type RM Length L Ch R = 1 ,3212    ,781.7,781.7,781.7
XS GIS Cut Line= 4
   2296644.58075724035.3933551992296554.41678755723947.459322686
2296469.48049853 723787.389198052295792.04844626723495.539749707
#Sta/Elev= 30
       0 1957.49    58.4 1956.98   100.9 1955.62   117.8 1954.03   123.8 1952.69
   137.6 1947.48   181.9  1927.4   190.5 1926.74   200.3 1924.55   214.6 1923.88
   228.1 1924.04   241.7 1926.12   246.3 1923.93   250.8 1922.42   259.8 1922.58
   264.4 1923.68   273.4 1928.49   292.9  1931.1   308.6 1929.58   403.7 1928.85
   552.5 1929.58     853 1935.17   879.1 1936.34   921.7 1940.39   935.8 1940.39
   940.1 1941.34   944.5 1945.58   948.8 1948.14   992.4 1953.29  1044.8 1955.53
#Mann= 10 ,-1,0
       0     .05       0      60      .1       0   246.3    .045       0
   264.4      .1       0  265.94     .06       0  487.15     .05       0
  697.15     .06       0  807.15     .07       0  917.15     .06       0
  947.15      .1       0
Bank Sta=246.3,264.4
XS Rating Curve= 0 ,0
Exp/Cntr(USF)=0,0
Exp/Cntr=0.3,0.1

Type RM Length L Ch R = 1 ,2431    ,313.5,313.5,313.5
XS GIS Cut Line= 3
2297401.71887063723711.6483317952297018.27142805723406.088650994
2295834.97658573723340.183621801
#Sta/Elev= 30
       0 1960.76    23.2  1960.8    39.9 1958.47      81 1939.08   201.4 1932.26
     353 1927.75   487.9 1927.77   520.4 1926.01   572.5 1926.98   648.5 1925.03
   748.8 1924.97   780.1 1925.89   792.9 1924.02   792.9    1924   800.9 1922.43
   820.9 1922.87   824.9 1923.89   832.9 1925.67   906.8 1924.46   945.5 1927.04
  1045.3 1926.02  1142.1 1928.65  1409.8 1930.22    1514 1932.69    1522 1933.32
    1538 1937.99  1562.1 1938.56  1578.5 1946.64  1598.1 1950.63  1675.4 1959.67
#Mann= 8 ,-1,0
       0      .1       0      20     .05       0   710.3      .1       0
   792.9    .045       0   824.9     .08       0  1010.3     .05       0
  1400.3     .06       0  1600.3      .1       0
#XS Ineff= 2 , 0
        565.8593    1931 1021.33          1929.3
Permanent Ineff=
       F       F
Bank Sta=792.9,824.9
XS Rating Curve= 0 ,0
Exp/Cntr(USF)=0,0
Exp/Cntr=0.3,0.1

Type RM Length L Ch R = 1 ,2117    ,513.8,513.8,513.8
XS GIS Cut Line= 3
2297417.99741284723110.3278497592297411.11322512723118.417506143
2295975.77369355723043.610990435
#Sta/Elev= 30
       0 1949.23    29.6 1950.56    77.7 1948.94   101.7  1941.8   141.7 1925.73
   149.7 1923.83   153.8 1923.89   165.8 1926.26   193.8 1926.83   205.8 1926.03
   257.9 1925.68   281.9 1924.29   299.8 1925.38   498.4 1925.78   554.3 1924.42
   694.5 1924.59   710.5 1924.33  715.16  1922.9   718.9 1921.81   734.5 1922.89
   738.5 1923.56   754.6 1922.84   878.7 1923.09  1072.9 1929.72    1191  1931.4
  1231.2  1933.5  1251.2 1932.84  1354.7 1934.99  1395.4 1938.19  1447.9 1937.02
#Mann= 6 ,-1,0
       0     .08       0  130.62     .05       0  715.16    .045       0
   734.5     .05       0 1120.62     .07       0 1420.62     .06       0
#XS Ineff= 2 , 0
             195    1931
Permanent Ineff=
       F       F
Bank Sta=715.16,734.5
XS Rating Curve= 0 ,0
Exp/Cntr(USF)=0,0
Exp/Cntr=0.3,0.1

Type RM Length L Ch R = 1 ,1603    ,607.1,607.1,607.1
XS GIS Cut Line= 2
2296810.87068638722601.1317955112296225.84034405722734.321504368
#Sta/Elev= 30
       0 1934.29     6.9 1933.39    32.4  1934.3    39.7 1934.33      52 1933.64
    59.1 1931.16    72.5 1924.87    84.8 1923.29   105.3 1922.54   158.7 1922.73
   179.2 1923.37   195.6 1923.06   207.9 1923.29  215.941922.162   220.2 1921.15
   228.4 1920.41   232.5 1921.14  234.31 1922.16   236.6 1923.46   239.5 1923.75
   249.6 1923.01   277.6 1922.51   309.7 1923.84   326.9 1923.31   367.9 1923.88
   436.7 1927.01   450.7 1926.73   480.1  1927.3   510.2 1928.33     600 1930.37
#Mann= 4 ,-1,0
       0     .08       0      20     .06       0  215.94    .045       0
  234.31     .07       0
Bank Sta=215.94,234.31
XS Rating Curve= 0 ,0
Exp/Cntr(USF)=0,0
Exp/Cntr=0.3,0.1

Type RM Length L Ch R = 1 ,996     ,65.1,65.1,65.1
XS GIS Cut Line= 5
2296694.35507753722491.883123796  2296574.861274 722366.01348726
2296457.71534725722320.9573615872296356.99391012722325.750489503
2296279.64858034 722342.68957912
#Sta/Elev= 30
       0 1931.82    32.2 1932.14      60 1931.22      92 1930.48     103 1928.64
   119.5 1924.69   127.9  1923.8   180.7 1924.24     187 1923.61  194.871921.531
   197.9 1920.36     201 1919.92   209.3 1919.53   213.4  1919.9  220.221921.531
   228.9 1922.63   312.6 1922.88   332.6 1923.73   358.1 1930.67   371.9 1933.78
   392.7 1936.57   408.9 1937.53   420.3 1939.51     427 1941.97   437.6 1947.92
   441.7 1949.43   449.9 1950.26   470.4  1949.7   474.4 1950.27   479.1 1953.18
#Mann= 7 ,-1,0
       0     .07       0      60     .08       0     140     .06       0
  194.87    .045       0  220.22     .08       0  359.07     .07       0
   459.9     .06       0
Bank Sta=194.87,220.22
XS Rating Curve= 0 ,0
Exp/Cntr(USF)=0,0
Exp/Cntr=0.3,0.1

Type RM Length L Ch R = 1 ,931     ,172.9,172.9,172.9
XS GIS Cut Line= 4
2296718.48110101722399.2305508182296633.43423737 722316.45174902
 2296381.1199336722233.0979165252296303.77460382722250.037006142
#Sta/Elev= 30
       0 1930.37    31.1 1932.15    53.5 1931.86      66 1930.09    81.4 1926.38
    87.9 1925.29   141.1 1925.54   163.4 1923.94   166.3 1923.49  170.24 1921.46
   174.8 1920.15     179 1919.74   187.4 1920.22  193.981921.464     200  1922.7
   216.9 1921.81   226.8 1922.46   280.1 1923.02     318 1924.44   326.4 1925.59
   339.1 1928.83   364.3 1936.82     377 1940.35   384.4 1941.66   398.7 1947.45
   405.4 1949.17   418.9 1950.42   430.4 1950.91   450.9 1951.05   463.6 1950.57
#Mann= 6 ,-1,0
       0      .1       0      30     .08       0  170.24    .045       0
  193.98     .08       0  358.68     .07       0  463.59      .1       0
Bank Sta=170.24,193.98
XS Rating Curve= 0 ,0
Exp/Cntr(USF)=0,0
Exp/Cntr=0.3,0.1

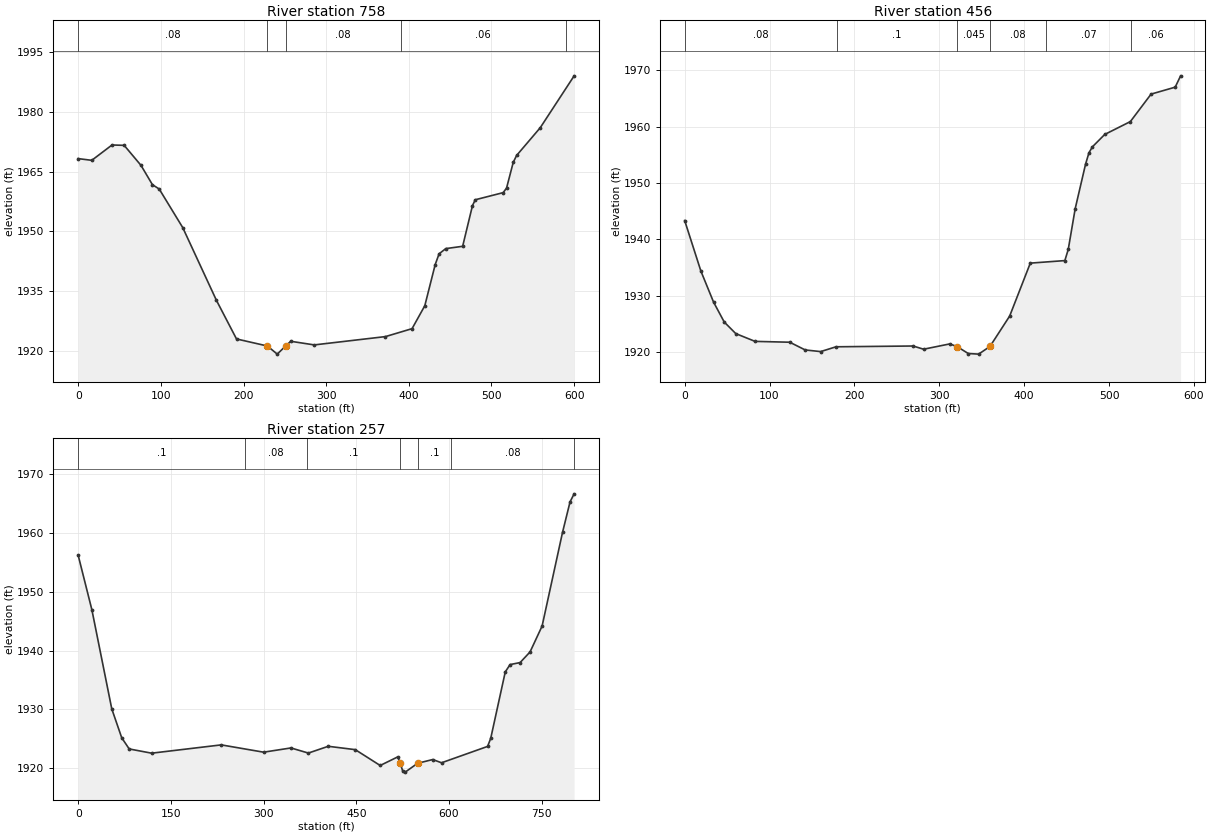
Type RM Length L Ch R = 1 ,758     ,302.2,302.2,302.2
XS GIS Cut Line= 2
2296784.25566109722186.4892981592296195.92477347722068.732061974
#Sta/Elev= 30
       0 1968.28    16.4 1967.85    40.9 1971.71    55.6 1971.62      76 1966.57
    89.8 1961.72      98 1960.63   126.5 1950.91   167.3 1932.59   191.5 1922.91
   228.9 1921.13   240.8 1919.09   251.2 1921.19   257.1 1922.32   285.6 1921.41
   371.7  1923.5   403.9  1925.5   419.3 1931.26   431.9 1941.63   436.6 1944.33
   444.7 1945.64   465.1 1946.22     477 1956.47   480.4 1957.93   514.1 1959.72
   518.2 1960.85   526.3 1967.34   530.4 1969.08     559 1976.06     600 1989.11
#Mann= 5 ,-1,0
       0     .08       0   228.9    .045       0   251.2     .08       0
     390     .06       0     590      .1       0
Bank Sta=228.9,251.2
XS Rating Curve= 0 ,0
Exp/Cntr(USF)=0,0
Exp/Cntr=0.3,0.1

Type RM Length L Ch R = 1 ,456     ,199.3,199.3,199.3
XS GIS Cut Line= 3
2296685.24878189722118.2047960582296559.09163001721883.912942558
2296245.95155658721827.592785467
#Sta/Elev= 30
       0 1943.34    19.1 1934.38      34 1928.89    46.6 1925.35    60.2  1923.3
    82.9 1921.92   123.8 1921.77     142  1920.4   160.2 1920.11   178.3 1920.96
   269.1  1921.1   281.5 1920.53   312.3 1921.47   320.8 1921.01   334.1 1919.77
   346.3 1919.66  359.671921.015   382.9 1926.41   407.2 1935.79   447.9 1936.24
   451.9 1938.21   460.1 1945.45   472.3 1953.33   476.3 1955.35   480.4 1956.41
   494.9  1958.6   525.1 1960.88   549.5 1965.75   577.9 1966.98   584.3 1968.99
#Mann= 6 ,-1,0
       0     .08       0     180      .1       0   320.8    .045       0
  359.67     .08       0   426.1     .07       0   526.1     .06       0
Bank Sta=320.8,359.67
XS Rating Curve= 0 ,0
Exp/Cntr(USF)=0,0
Exp/Cntr=0.3,0.1

Type RM Length L Ch R = 1 ,257     ,,,
XS GIS Cut Line= 3
2296729.28584256722131.1546894632296680.74316933721710.446858717
2296305.55307264721657.200435059
#Sta/Elev= 30
       0 1956.17    22.1 1946.94    54.3 1930.09    70.4 1925.18    82.5 1923.28
   118.8 1922.56   231.5 1923.97     300 1922.73   344.2 1923.45   372.4 1922.58
   404.6 1923.73   448.3 1923.16   488.6 1920.47     517 1921.93     521 1920.88
   525.1 1919.51   529.1 1919.34  549.071920.839   573.6 1921.48   587.9 1920.93
   662.4 1923.71   667.5  1925.1     691 1936.38   698.8 1937.62     715 1937.96
   731.1 1939.77   750.6 1944.17   783.6 1960.07   795.8 1965.27   802.4 1966.64
#Mann= 7 ,-1,0
       0      .1       0     270     .08       0     370      .1       0
     521    .045       0  549.07      .1       0   603.5     .08       0
  802.45     .07       0
Bank Sta=521,549.07
XS Rating Curve= 0 ,0
Exp/Cntr(USF)=0,0
Exp/Cntr=0.3,0.1
LCMann Table=0

Chan Stop Cuts=-1
Use User Specified Reach Order=0
Composite Channel Slope=5